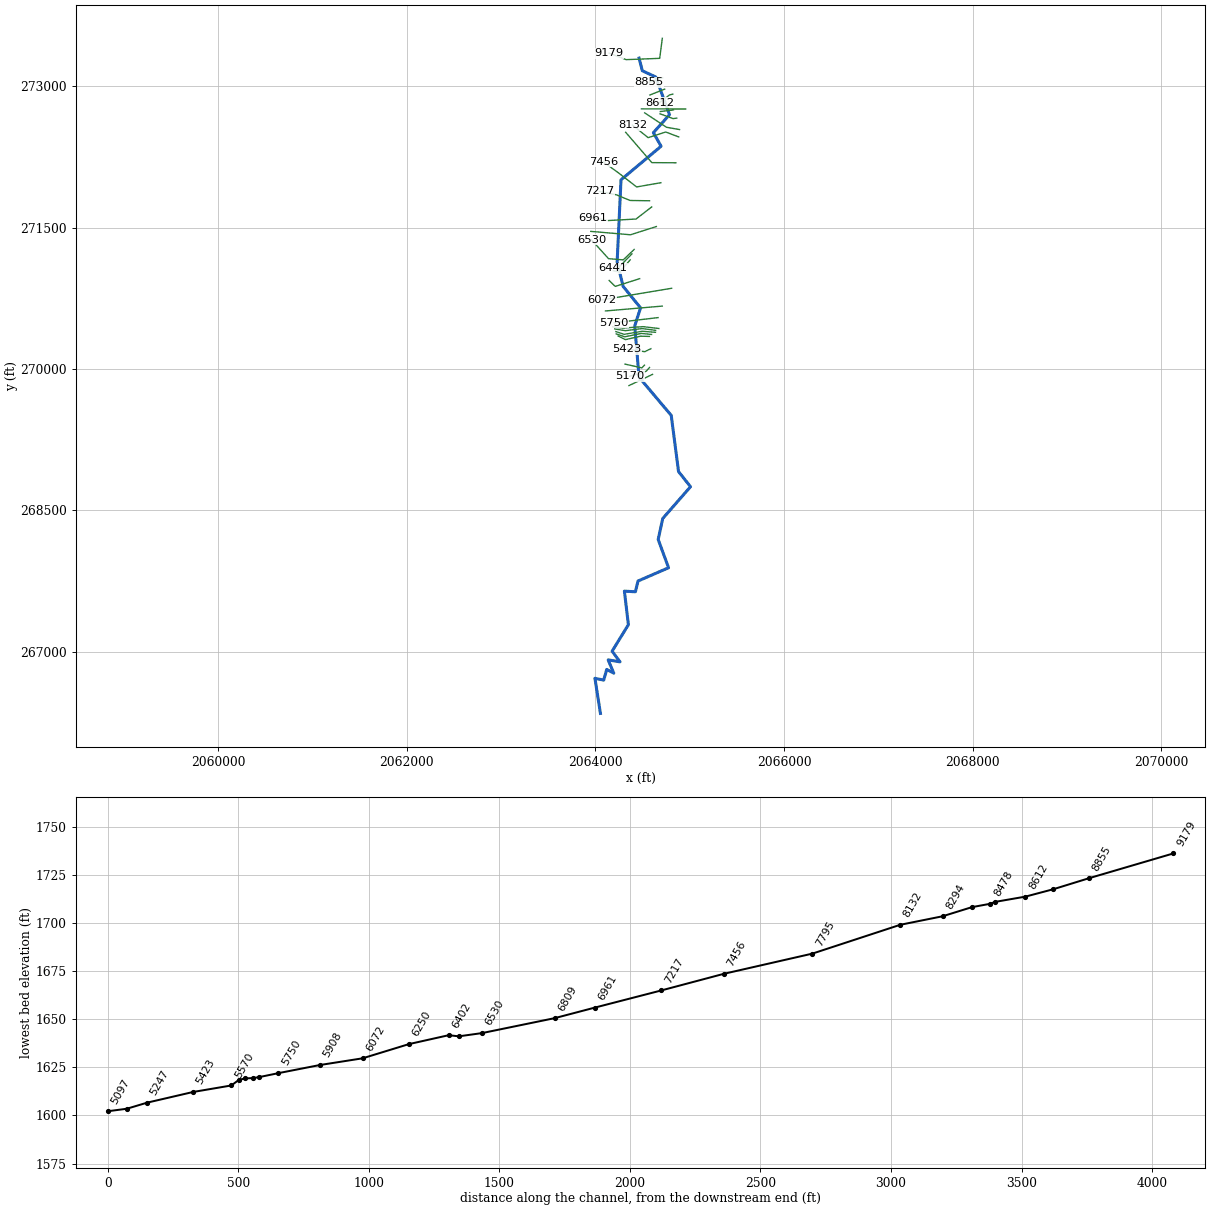
--- GREENBRRV_T1.prj (project) ---

Proj Title=GREENBRRV_T1
Current Plan=p01
Default Exp/Contr=0,0
English Units
Geom File=g01
Flow File=f01
Plan File=p01
BEGIN DESCRIPTION:
Stream Name: Greenrbrier River Tributary 1
Flood Zone: Approximate
Summers County, West Virginia
HEC-RAS Version: 5.0.7
Hydrology Method:
regression
Model Notes:
END DESCRIPTION:
DSS Export Rating Curves= 0
DSS Export Rating Curve Sorted= 0
DSS Export Volume Flow Curves= 0
DXF OffsetX= 0
DXF OffsetY= 0
DXF ScaleX= 0
DXF ScaleY= 0

--- GREENBRRV_T1.p01 (plan) ---

Plan Title=Floodplain
Program Version=5.07
Short Identifier=Floodplain
Geom File=g01
Flow File=f01
Subcritical Flow
K Sum by GR= 0
Std Step Tol= 0.01
Critical Tol= 0.01
Num of Std Step Trials= 20
Max Error Tol= 0.3
Flow Tol Ratio= 0.001
Split Flow NTrial= 30
Split Flow Tol= 0.02
Split Flow Ratio= 0.02
Log Output Level= 0
Friction Slope Method= 1
Unsteady Friction Slope Method= 2
Unsteady Bridges Friction Slope Method= 1
Parabolic Critical Depth
Global Vel Dist= 0 , 0 , 0
Global Log Level= 0
CheckData=True
Encroach Param=-1 ,0,0, 0
Mapping Interval=1HOUR
Computation Time Step Use Courant=        0
Computation Time Step Use Time Series=    0
Computation Time Step Count To Double=0
Computation Time Step Max Doubling=0
Computation Time Step Max Halving=0
Computation Time Step Residence Courant=0
Run HTab= 0
Run UNet= 0
Run Sediment= 0
Run PostProcess= 0
Run WQNet= 0
Run RASMapper= 0
UNET Theta= 0
UNET Theta Warmup= 0
UNET ZTol= 0
UNET ZSATol= 0
UNET MxIter= 0
UNET Max Iter WO Improvement= 0
UNET MaxInSteps= 0
UNET DtIC= 0
UNET DtMin= 0
UNET MaxCRTS= 0
UNET WFStab= 0
UNET SFStab= 0
UNET WFX= 1
UNET SFX= 1
UNET 1D Methodology=Finite Difference
UNET DSS MLevel= 1
UNET Pardiso=0
UNET DZMax Abort= 0
UNET Use Existing IB Tables= 0
UNET Froude Reduction=False
UNET Froude Limit= 0
UNET Froude Power= 0
UNET D1 Cores= 0
UNET D2 Coriolis=0
UNET D2 Cores= 0
UNET D2 Theta= 1
UNET D2 Theta Warmup= 1
UNET D2 Z Tol= 0.01
UNET D2 Volume Tol= 0.01
UNET D2 Max Iterations= 20
UNET D2 Equation= 0
UNET D2 RampUpFraction=0.1
UNET D2 TimeSlices= 1
UNET D2 BCVolumeCheck=0
UNET D1D2 MaxIter= 0
UNET D1D2 ZTol=0.01
UNET D1D2 QTol=0.1
UNET D1D2 MinQTol=1
Write IC File= 0
Write IC File at Fixed DateTime=0
Write IC File at Sim End=0
Echo Input=False
Echo Parameters=False
Echo Output=False
Write Detailed= 0
HDF Write Warmup=0
HDF Write Time Slices=0
HDF Flush=0
HDF Face Node Velocities=0
HDF Compression= 1
HDF Chunk Size= 1
HDF Spatial Parts= 1
HDF Use Max Rows=0
HDF Fixed Rows= 1
Calibration Method= 0
Calibration Iterations= 20
Calibration Max Change=0.05
Calibration Tolerance=0.2
Calibration Maximum=1.5
Calibration Minimum=0.5
Calibration Optimization Method= 1
WQ AD Non Conservative
WQ ULTIMATE=-1
WQ Max Comp Step=1HOUR
WQ Output Interval=15MIN
WQ Output Selected Increments= 0
WQ Output face flow=0
WQ Output face velocity=0
WQ Output face area=0
WQ Output face dispersion=0
WQ Output cell volume=0
WQ Output cell surface area=0
WQ Output cell continuity=0
WQ Output cumulative cell continuity=0
WQ Output face conc=0
WQ Output face dconc_dx=0
WQ Output face courant=0
WQ Output face peclet=0
WQ Output face adv mass=0
WQ Output face disp mass=0
WQ Output cell mass=0
WQ Output cell source sink temp=0
WQ Output nsm pathways=0
WQ Output nsm derived pathways=0
WQ Output MaxMinRange=-1
WQ Daily Max Min Mean=-1
WQ Daily Range=0
WQ Daily Time=0
WQ Create Restart=0
WQ Fixed Restart=0
WQ System Summary=0
WQ Write To DSS=0
WQ Use Fixed Temperature=0
Sorting and Armoring Iterations= 10
XS Update Threshold= 0.02
Bed Roughness Predictor= 0
Hydraulics Update Threshold= 0.02
Energy Slope Method= 1
Volume Change Method= 1
Sediment Retention Method= 0
XS Weighting Method= 0
Number of US Weighted Cross Sections= 1
Number of DS Weighted Cross Sections= 1
Upstream XS Weight=0
Main XS Weight=1
Downstream XS Weight=0
Number of DS XS's Weighted with US Boundary= 1
Upstream Boundary Weight= 1
Weight of XSs Associated with US Boundary= 0
Number of US XS's Weighted with DS Boundary= 1
Downstream Boundary Weight= 0.5
Weight of XSs Associated with DS Boundary= 0.5
Percentile Method= 0
Sediment Output Level= 3
Mass or Volume Output= 0
Output Increment Type= 1
Profile and TS Output Increment= 1
XS Output Flag= 0
XS Output Increment= 10
Write Gradation File= 0
Read Gradation Hotstart= 0
Write HDF5 File= 1
Write Binary Output= 1
Write DSS Sediment File= 0
SV Curve= 0
Specific Gage Flag= 0

--- GREENBRRV_T1.f01 (steady flow) ---

Flow Title=Flows
Program Version=5.07
Number of Profiles= 6
Profile Names=01pct,10pct,04pct,02pct,0_2pct,01plus
River Rch & RM=GREENBRRV_T1,Main            ,9179
     448     235     314     379     629     663
River Rch & RM=GREENBRRV_T1,Main            ,6441
     506     266     355     428     709     749
River Rch & RM=GREENBRRV_T1,Main            ,4465
     592     313     416     501     826     875
Boundary for River Rch & Prof#=GREENBRRV_T1,Main            , 1
Up Type= 0
Dn Type= 3
Dn Slope=0.00912
Boundary for River Rch & Prof#=GREENBRRV_T1,Main            , 2
Up Type= 0
Dn Type= 3
Dn Slope=0.00912
Boundary for River Rch & Prof#=GREENBRRV_T1,Main            , 3
Up Type= 0
Dn Type= 3
Dn Slope=0.00912
Boundary for River Rch & Prof#=GREENBRRV_T1,Main            , 4
Up Type= 0
Dn Type= 3
Dn Slope=0.00912
Boundary for River Rch & Prof#=GREENBRRV_T1,Main            , 5
Up Type= 0
Dn Type= 3
Dn Slope=0.00912
Boundary for River Rch & Prof#=GREENBRRV_T1,Main            , 6
Up Type= 0
Dn Type= 3
Dn Slope=0.00912
DSS Import GetInterval= 0
DSS Import GetPeak= 0
DSS Import FillOption= 0

--- GREENBRRV_T1.g01 (geometry) ---

Geom Title=Geometry
Program Version=5.07

River Reach=GREENBRRV_T1    ,Main
Reach XY= 30
     2064463.576      273297.344     2064497.951       273163.49
     2064639.618      273097.865     2064786.493      272697.865
     2064615.138      272506.719     2064696.909      272362.969
     2064271.909      272006.719     2064230.764      271134.844
     2064294.826       270875.99     2064479.201      270648.907
     2064417.439       270457.24     2064463.446      269912.969
     2064804.591      269508.455     2064882.142      268912.022
     2065009.298       268752.12     2064714.594      268414.881
     2064666.011      268192.654     2064776.457      267892.447
     2064452.493      267752.169     2064424.503      267637.717
     2064307.836      267644.661     2064350.197      267288.411
     2064177.511      267007.814     2064261.308      266894.661
     2064135.614      266915.494     2064195.336      266774.522
     2064120.336      266814.106     2064088.392      266700.911
     2063995.336      266720.356     2064053.659      266348.182

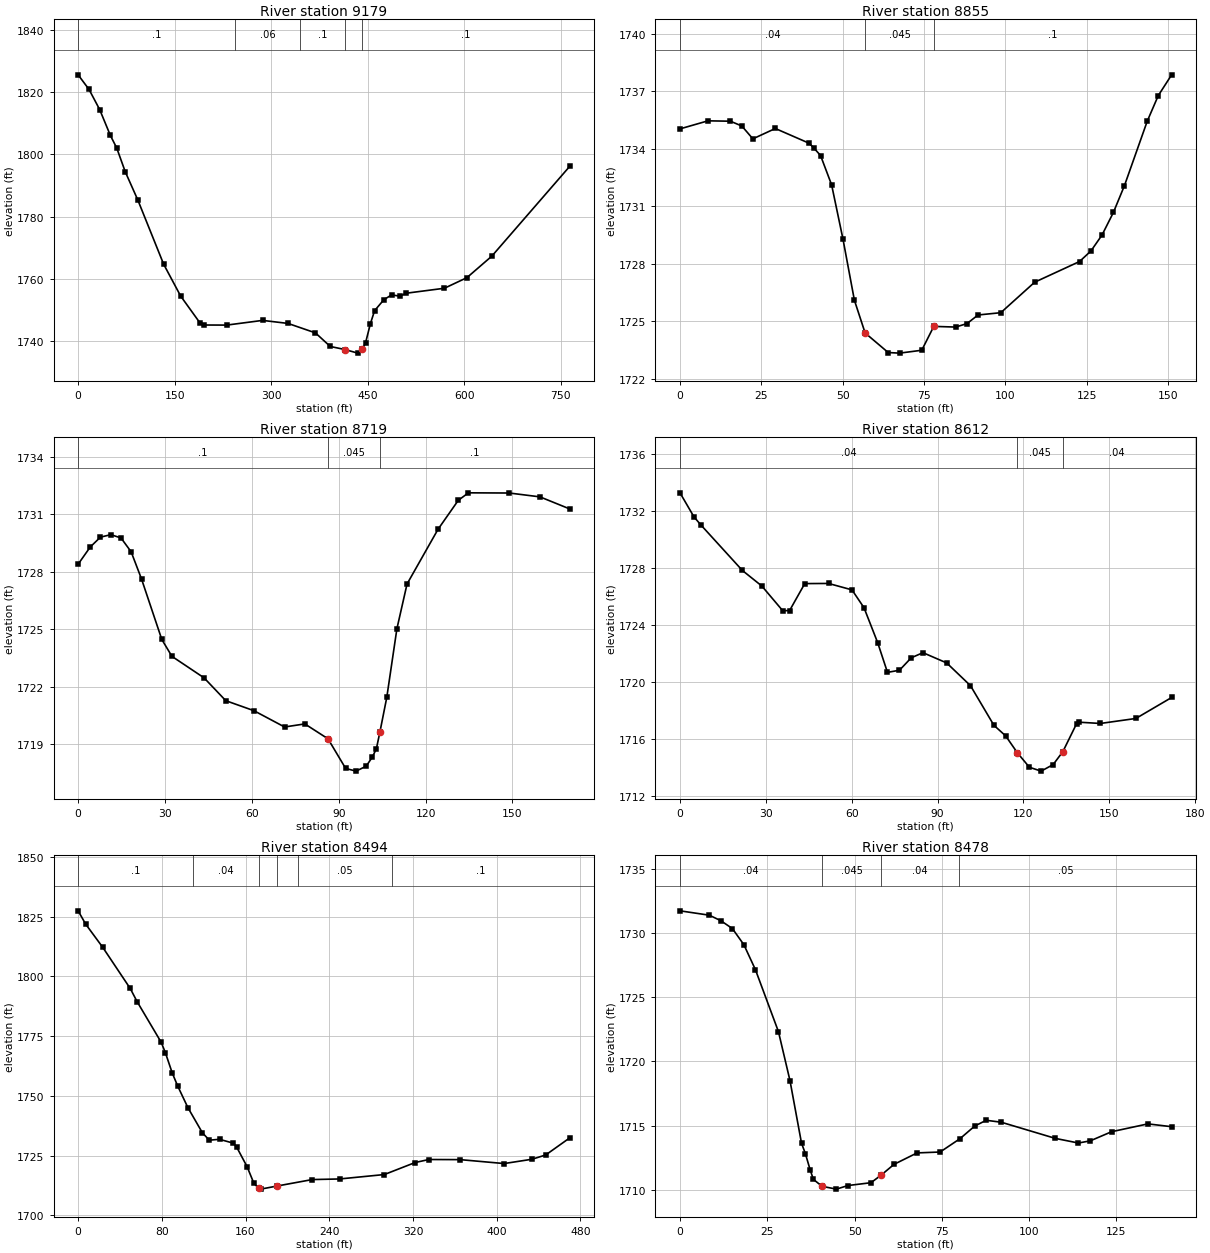
Type RM Length L Ch R = 1 ,9179    ,323.5,323.5,323.5
XS GIS Cut Line= 4
2064709.98879132273507.3515179862064682.25453806273295.184480601
2064325.86938376273281.3173539742064145.59673762273350.652987107
#Sta/Elev= 30
       0 1825.58      17 1820.87    33.5 1814.42    50.1 1806.11      60 1802.07
    73.2 1794.46    92.8 1785.36   132.8  1764.8   159.3 1754.54     189 1746.01
   195.7 1745.25   230.8 1745.22   286.6 1746.73     326 1745.76   368.7 1742.72
   391.7 1738.36     415 1737.35   434.4 1736.22   441.7 1737.44   446.6 1739.57
   454.1  1745.7   460.6 1749.87     475 1753.37   486.9 1754.91     500 1754.52
   509.9 1755.46     569 1757.05     604 1760.45   642.7 1767.36   763.8 1796.21
#Mann= 5 ,-1 , 0
       0      .1       0  243.97     .06       0  343.97      .1       0
     415    .045       0   441.7      .1       0
Bank Sta=415,441.7
XS Rating Curve= 0 ,0
Exp/Cntr(USF)=0,0
Exp/Cntr=0.3,0.1

Type RM Length L Ch R = 1 ,8855    ,135.8,136.5,136
XS GIS Cut Line= 2
2064712.92428149273088.8870821732064569.68923166273040.714342101
#Sta/Elev= 30
       0 1735.03     8.6 1735.45    15.5 1735.43      19 1735.18    22.4 1734.51
    29.3 1735.05    39.7 1734.28    41.2 1734.02    43.2 1733.64    46.6 1732.11
    50.1 1729.27    53.6 1726.09    56.91724.381      64 1723.36    67.5 1723.33
    74.3 1723.48      781724.725    84.7 1724.69    88.2 1724.87    91.6 1725.32
    98.6 1725.44     109 1727.03   122.8 1728.11   126.3 1728.66   129.7 1729.49
   133.2 1730.67   136.6 1732.07   143.6 1735.43     147 1736.77   151.1 1737.85
#Mann= 3 ,-1 , 0
       0     .04       0    56.9    .045       0      78      .1       0
Bank Sta=56.9,78
XS Rating Curve= 0 ,0
Exp/Cntr(USF)=0,0
Exp/Cntr=0.3,0.1

Type RM Length L Ch R = 1 ,8719    ,102.8,106.9,110.6
XS GIS Cut Line= 2
2064734.95312415272968.8728887432064577.12040186272906.254471749
#Sta/Elev= 30
       0 1728.39     4.2 1729.29     7.7  1729.8    11.3 1729.93    14.8 1729.76
    18.3 1729.04    21.9 1727.62    28.9 1724.47    32.4 1723.59    43.5 1722.47
      51 1721.28    60.7 1720.76    71.3 1719.91    78.3 1720.07    86.31719.294
    92.4 1717.75      96 1717.61    99.5 1717.87   101.6 1718.34     103 1718.77
   104.21719.626   106.6 1721.45   110.1 1725.03   113.6 1727.36   124.3 1730.21
   131.3 1731.72   134.8 1732.11   148.9  1732.1   159.5  1731.9   169.8 1731.27
#Mann= 3 ,-1 , 0
       0      .1       0    86.3    .045       0   104.2      .1       0
Bank Sta=86.3,104.2
XS Rating Curve= 0 ,0
Exp/Cntr(USF)=0,0
Exp/Cntr=0.3,0.1

Type RM Length L Ch R = 1 ,8612    ,125,117.6,107.4
XS GIS Cut Line= 3
2064821.13530562272915.7582546692064787.02315922272907.472588435
2064678.42997635 272824.43074271
#Sta/Elev= 30
       0 1733.26     4.9 1731.57     7.3 1731.01    21.8 1727.82    28.6 1726.73
    35.9    1725    38.3 1725.01    43.6  1726.9    51.9 1726.91    60.1 1726.46
    64.3 1725.21    69.1 1722.75    72.5 1720.68    76.7 1720.83    80.8  1721.7
    84.9 1722.06    93.2 1721.34   101.5 1719.75   109.7 1716.97   113.8 1716.23
   117.91715.043   122.1 1714.03   126.2 1713.76   130.4 1714.22   133.8 1715.13
   138.6 1717.09   139.3 1717.19   146.9  1717.1   159.3 1717.45   171.8 1718.92
#Mann= 3 ,-1 , 0
       0     .04       0   117.9    .045       0   133.8     .04       0
Bank Sta=117.9,133.8
XS Rating Curve= 0 ,0
Exp/Cntr(USF)=0,0
Exp/Cntr=0.3,0.1

Type RM Length L Ch R = 1 ,8494    ,15,16.4,18.3
XS GIS Cut Line= 2
2064958.03918597272757.8571981232064488.25213007272759.392449939
#Sta/Elev= 30
       0 1827.42     7.2 1821.86    23.6  1812.1    49.8 1794.93    56.4  1789.4
    79.4  1772.4    83.4 1768.04    89.9 1759.63      95 1754.26   104.9 1745.08
   118.7  1734.6   125.3 1731.47   135.1 1731.83   148.3 1730.22   151.5 1728.57
   161.4 1720.43   167.9 1713.49   172.51711.344   174.5 1710.99   189.71712.256
   223.7 1714.99   249.8 1715.24   292.6 1717.09   322.1 1722.13   335.2 1723.38
     365 1723.33   407.1 1721.69   433.7 1723.49   446.8 1725.28   469.8 1732.44
#Mann= 6 ,-1 , 0
       0      .1       0     110     .04       0   172.5    .045       0
   189.7     .04       0     210     .05       0     300      .1       0
Bank Sta=172.5,189.7
XS Rating Curve= 0 ,0
Exp/Cntr(USF)=0,0
Exp/Cntr=0.3,0.1

Type RM Length L Ch R = 1 ,8478    ,76.6,71.3,63.6
XS GIS Cut Line= 2
2064827.98007378272747.7784095632064688.16086871272731.051572147
#Sta/Elev= 30
       0 1731.73     8.4 1731.39    11.7 1730.96      15 1730.35    18.3 1729.09
    21.6 1727.15    28.2 1722.32    31.5 1718.51    34.8 1713.64    35.9 1712.83
    37.3 1711.54    38.2 1710.82    40.71710.277    44.8 1710.06    48.1 1710.34
    54.7 1710.56    57.61711.149    61.3 1711.99    67.9 1712.88    74.5 1712.95
    80.2 1713.99    84.4 1714.97    87.7 1715.42      92 1715.27   107.5 1714.01
   114.1 1713.65   117.5 1713.82   123.6 1714.53     134 1715.14   140.8 1714.92
#Mann= 4 ,-1 , 0
       0     .04       0    40.7    .045       0    57.6     .04       0
      80     .05       0
Bank Sta=40.7,57.6
XS Rating Curve= 0 ,0
Exp/Cntr(USF)=0,0
Exp/Cntr=0.3,0.1

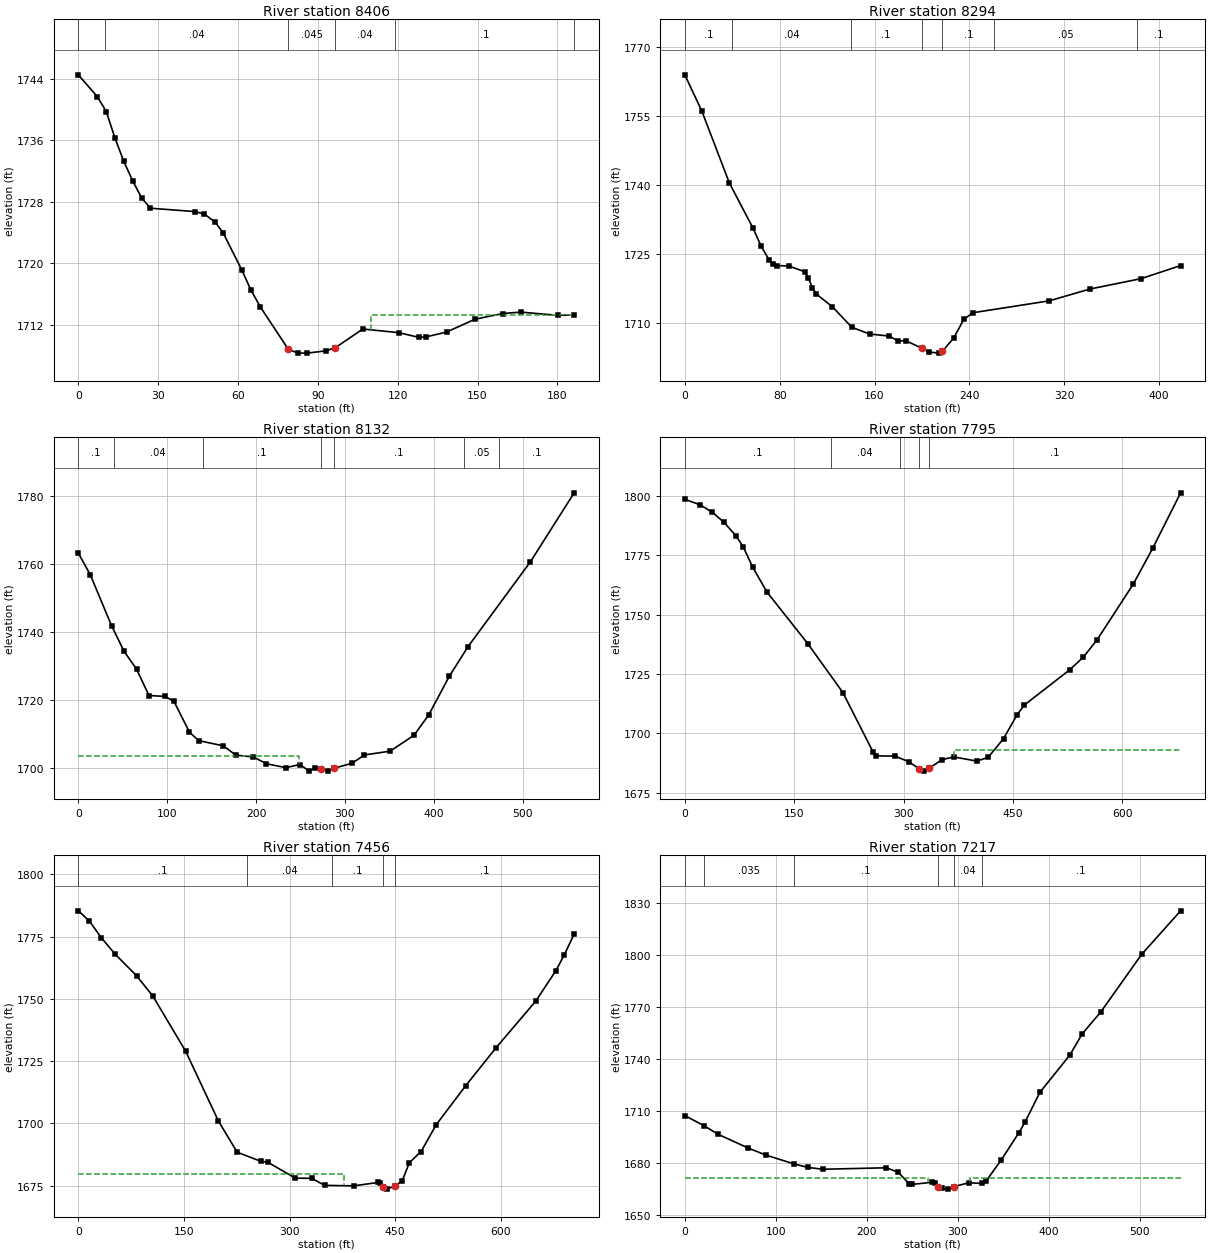
Type RM Length L Ch R = 1 ,8406    ,113.4,112.3,107.2
XS GIS Cut Line= 3
 2064862.8570057272661.2126099712064824.07259808272655.791917545
2064686.09537749272706.894591838
#Sta/Elev= 30
       0 1744.52     7.2 1741.65    10.5 1739.74    13.8 1736.24    17.1 1733.24
    20.5 1730.66    23.8 1728.48    27.1 1727.15    43.9 1726.71    47.4 1726.38
    51.4 1725.34    54.4 1723.95    61.4 1719.12    64.9 1716.46    68.4 1714.29
    78.9 1708.78    82.4 1708.29    85.9 1708.28    92.9 1708.57    96.4 1708.95
   106.9 1711.42   120.3 1710.95   127.9 1710.34   130.5 1710.38   138.4 1711.03
   148.9 1712.68   159.4 1713.44   166.4 1713.62   180.3 1713.19   186.3 1713.25
#Mann= 6 ,-1 , 0
       0      .1       0      10     .04       0    78.9    .045       0
    96.4     .04       0  119.16      .1       0   186.3     .05       0
#XS Ineff= 2 , 0
                          110.14         1713.24
Permanent Ineff=
       F       F
Bank Sta=78.9,96.4
XS Rating Curve= 0 ,0
Exp/Cntr(USF)=0,0
Exp/Cntr=0.3,0.1

Type RM Length L Ch R = 1 ,8294    ,147.3,162.2,168.9
XS GIS Cut Line= 3
2064892.79098377272539.8514401532064753.85069436 272564.41546922
2064522.79529594272717.173024981
#Sta/Elev= 30
       0 1764.02    14.3 1756.19    37.6  1740.5    57.6 1730.67    64.3 1726.83
      71 1723.81    74.3  1722.9    77.6 1722.56    87.6 1722.49     101 1721.24
   104.3 1719.87   107.6 1717.67   110.9 1716.38   124.3 1713.65   140.9 1709.15
   155.8 1707.69   172.4 1707.25   179.5 1706.23   186.6 1706.21   199.71704.626
   205.6  1703.8   214.1 1703.54   217.21703.934   226.9 1706.88   235.3 1710.91
   243.2 1712.33   307.4 1714.91   341.5 1717.46   384.8 1719.73   418.1 1722.57
#Mann= 7 ,-1 , 0
       0      .1       0      40     .04       0     140      .1       0
   199.7    .045       0   217.2      .1       0  261.09     .05       0
  381.09      .1       0
Bank Sta=199.7,217.2
XS Rating Curve= 0 ,0
Exp/Cntr(USF)=0,0
Exp/Cntr=0.3,0.1

Type RM Length L Ch R = 1 ,8132    ,349.1,336.8,323.3
XS GIS Cut Line= 4
2064884.11824037272461.6017552352064746.14101978272513.981996384
2064559.61625862272453.9363540912064392.25500031272588.080874108
#Sta/Elev= 30
       0 1763.23    13.4 1756.89    37.4 1741.88    51.4 1734.38    65.5 1729.12
    79.5 1721.35    97.1 1721.09   107.5  1719.7   125.1 1710.53   135.5 1708.08
   163.1 1706.55   177.2 1703.84     197 1703.26   211.7 1701.29   233.5 1700.13
   249.2 1701.05     260 1699.11   266.8 1700.14   272.6 1699.86   280.6 1699.22
   287.5 1699.93   308.2 1701.45     322 1703.87   350.9 1704.98   377.8 1709.67
   394.2 1715.58   417.5 1727.01   438.5  1735.7   508.8 1760.69     558 1780.96
#Mann= 7 ,-1 , 0
       0      .1       0      40     .04       0     140      .1       0
   272.6    .045       0   287.5      .1       0  433.54     .05       0
  473.54      .1       0
#XS Ineff= 2 , 0
          248.11 1703.67
Permanent Ineff=
       F       F
Bank Sta=272.6,287.5
XS Rating Curve= 0 ,0
Exp/Cntr(USF)=0,0
Exp/Cntr=0.3,0.1

Type RM Length L Ch R = 1 ,7795    ,334.9,338.9,340.2
XS GIS Cut Line= 3
2064853.71043086272187.5605812442064598.62378057272189.272572185
2064321.28124804272511.126869195
#Sta/Elev= 30
       0 1798.62      21 1796.27    37.4 1793.21    53.9 1788.88    70.2 1783.19
      80 1778.64    93.1 1770.03   112.8 1759.49   168.6 1737.84   216.8 1717.21
     258 1692.28   262.1 1690.57   288.1 1690.43   306.9 1688.14   320.8 1685.19
   327.8 1684.12   334.8 1685.28     353 1688.97   368.9 1690.09   400.7 1688.33
   416.2 1689.98   437.1 1697.81   455.7 1707.83   465.6 1711.94   527.9  1726.8
   546.5 1732.11   565.3 1739.36   615.1  1762.9   641.9 1778.09     680 1801.33
#Mann= 5 ,-1 , 0
       0      .1       0     200     .04       0  295.09      .1       0
   320.8    .045       0   334.8      .1       0
#XS Ineff= 2 , 0
                          369.52         1692.84
Permanent Ineff=
       F       F
Bank Sta=320.8,334.8
XS Rating Curve= 0 ,0
Exp/Cntr(USF)=0,0
Exp/Cntr=0.3,0.1

Type RM Length L Ch R = 1 ,7456    ,235.3,239,242.5
XS GIS Cut Line= 4
2064694.03574539271976.0424600792064437.60161602271931.340663504
2064246.65001604272079.2874747632064083.21949112272198.411250384
#Sta/Elev= 30
       0 1785.34    15.7 1781.25    32.4 1774.62    52.4 1767.91    82.6 1759.29
   105.6 1751.23   152.3 1729.03   198.9 1700.99   225.5 1688.46   258.8 1684.83
   269.2 1684.39   308.3 1678.02   331.2 1677.98   349.8 1675.14   390.8 1674.94
   425.9 1676.31   428.2 1676.23   432.8 1674.49   438.3 1673.63   449.4 1674.88
   459.8 1676.89   470.1 1684.26   486.7  1688.7   508.2 1699.48     550 1715.11
   592.6 1730.19   649.5 1749.07   677.9 1761.22   690.1 1767.63   704.1 1776.07
#Mann= 5 ,-1 , 0
       0      .1       0     240     .04       0   360.3      .1       0
   432.8    .045       0   449.4      .1       0
#XS Ineff= 2 , 0
          376.79 1679.52
Permanent Ineff=
       F       F
Bank Sta=432.8,449.4
XS Rating Curve= 0 ,0
Exp/Cntr(USF)=0,0
Exp/Cntr=0.3,0.1

Type RM Length L Ch R = 1 ,7217    ,246.1,256.3,259.7
XS GIS Cut Line= 4
2064574.27466012271784.7132342242064368.34365839271787.817721687
2064222.43274761271847.8378126442064044.44213305271883.022003894
#Sta/Elev= 30
       0 1707.47      21 1701.63    36.8 1696.61    69.6 1688.74    89.3 1684.63
   120.1 1679.56   135.2 1677.55   151.6 1676.48   221.7 1677.33   234.7 1674.73
   246.6 1668.22   250.1 1667.77   271.4 1668.93   274.9 1668.28   278.5 1666.51
   282.4 1665.42   289.1 1665.01   296.2 1666.51   312.6 1668.73   326.5 1668.28
   331.7 1669.93   347.8 1681.74     367 1697.24     374 1703.57   390.4 1720.82
   423.3 1742.32   437.2 1754.79   457.3 1767.18   502.4 1800.53   545.2 1825.62
#Mann= 6 ,-1 , 0
       0      .1       0      21    .035       0   120.1      .1       0
   278.5    .045       0   296.2     .04       0   326.5      .1       0
#XS Ineff= 2 , 0
       0  267.62 1671.52     314       0 1671.52
Permanent Ineff=
       F       F
Bank Sta=278.5,296.2
XS Rating Curve= 0 ,0
Exp/Cntr(USF)=0,0
Exp/Cntr=0.3,0.1

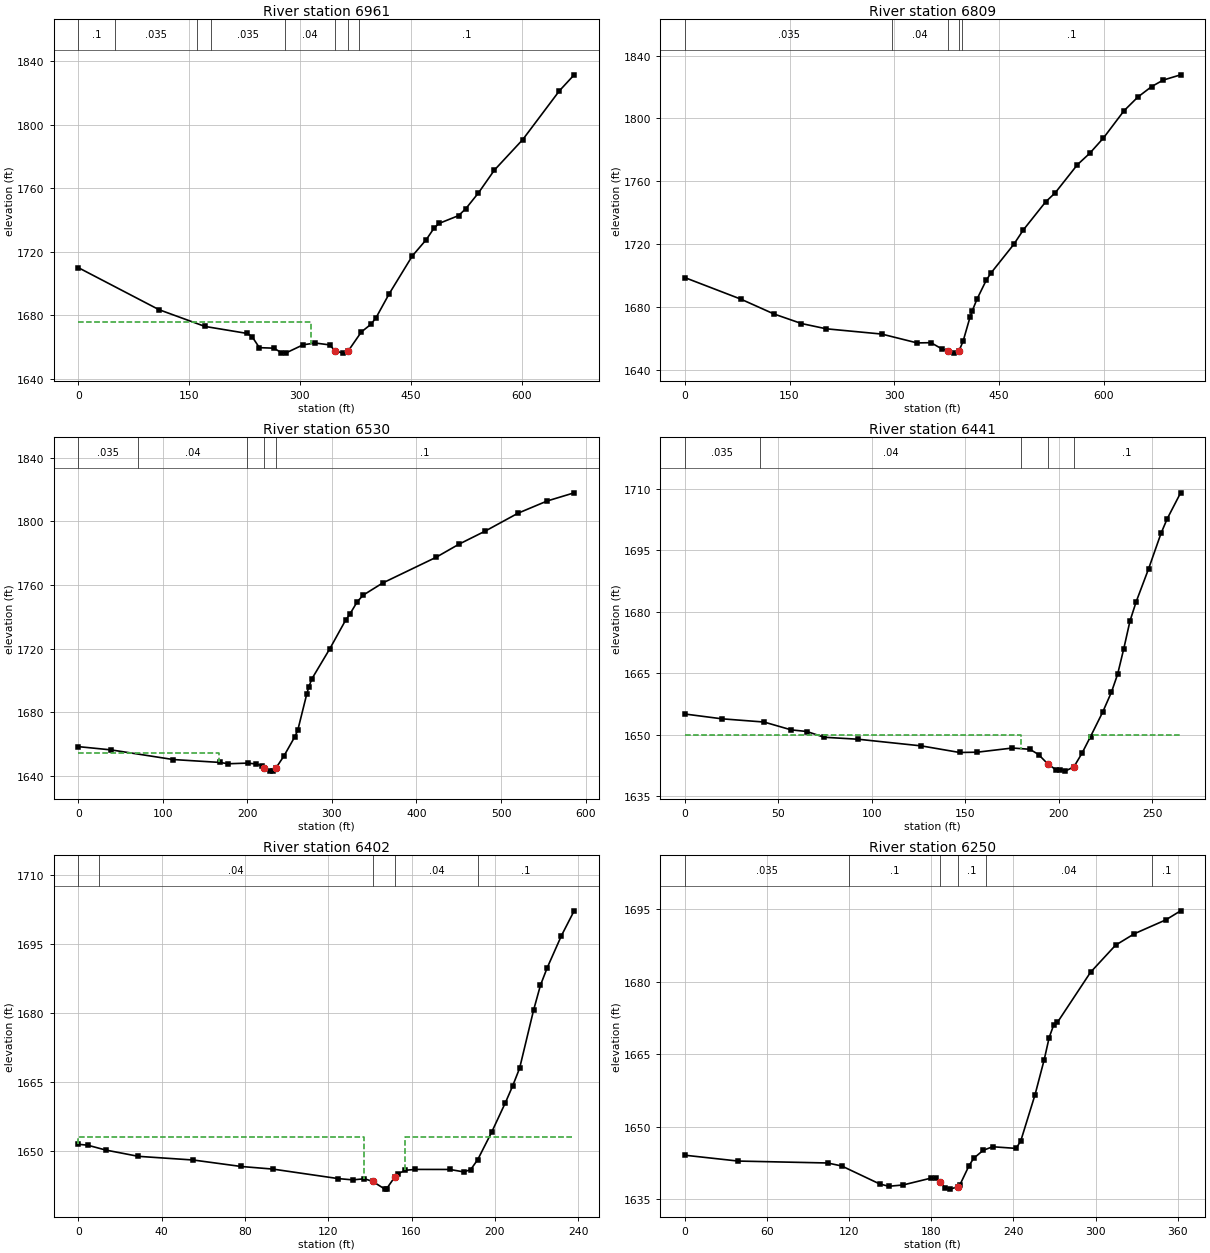
Type RM Length L Ch R = 1 ,6961    ,154.7,152.6,151
XS GIS Cut Line= 5
2064597.62526102271719.4580304772064431.07843225271590.868677766
2064133.56447596271574.7781460892064091.40159351  271583.9439901
2063973.44869284271604.367096967
#Sta/Elev= 30
       0 1709.88   109.2  1683.4   171.3 1672.86   228.7 1668.42   235.3 1666.33
   245.1 1659.47   264.9 1659.15   274.7 1656.31   281.3  1656.2   304.3 1661.28
   320.7 1662.39   340.4 1661.21   347.41657.462   358.3 1656.03   364.9 1657.08
   383.1 1669.36   396.1  1674.2   402.9 1678.26   420.8 1693.41   452.1 1717.26
   470.9 1727.47   481.7 1734.89   488.3 1737.74   514.7 1742.66   524.4 1746.97
   541.6 1756.94   563.2 1771.33   601.6 1790.56   651.3 1821.34   671.2 1831.36
#Mann= 8 ,-1 , 0
       0      .1       0      50    .035       0     160      .1       0
     180    .035       0  280.41     .04       0   347.4    .045       0
   364.9     .04       0  380.41      .1       0
#XS Ineff= 2 , 0
          314.31 1675.38
Permanent Ineff=
       F       F
Bank Sta=347.4,364.9
XS Rating Curve= 0 ,0
Exp/Cntr(USF)=0,0
Exp/Cntr=0.3,0.1

Type RM Length L Ch R = 1 ,6809    ,278.1,278.5,278
XS GIS Cut Line= 3
2064646.55952693271511.3241593352064372.64097629271424.012621317
2063951.49120467271459.964431089
#Sta/Elev= 30
       0 1698.68    80.1 1684.99   127.9 1675.48   167.1 1669.43   202.5 1666.08
     282 1662.73   332.8 1657.09   352.6 1657.24     369 1653.08   377.1 1652.16
   385.5 1650.59   392.5  1651.7   398.7 1658.29   408.5 1673.41   411.8 1677.56
   418.4 1684.82   431.6 1696.84   438.3 1701.44   471.1 1719.75   485.1 1729.13
   516.9 1746.89   530.4 1752.55   562.4 1770.56   579.8  1777.7   599.5 1787.44
   629.1 1804.85   648.9 1813.58   668.6 1820.24   685.1 1824.37   710.2 1827.74
#Mann= 5 ,-1 , 0
       0    .035       0   297.5     .04       0   377.1    .045       0
   392.5     .04       0   397.5      .1       0
Bank Sta=377.1,392.5
XS Rating Curve= 0 ,0
Exp/Cntr(USF)=0,0
Exp/Cntr=0.3,0.1

Type RM Length L Ch R = 1 ,6530    ,77.7,88.8,98.9
XS GIS Cut Line= 4
  2064411.212938271268.1393387182064295.56129133271157.736291865
2064139.81020824271170.6379619692063958.33916843271370.940902129
#Sta/Elev= 30
       0 1658.24    38.6  1656.2   112.2 1650.12   167.3  1648.3   177.2 1647.46
   200.3 1647.87   210.1 1647.32   216.7 1646.32   219.21644.835   226.6 1642.82
   229.9 1642.93   233.41644.487   243.1 1652.26   256.2 1664.59   259.5 1668.43
   270.2 1691.35   272.7 1695.94   276.3 1700.98   297.6 1719.99   316.2 1737.91
     321 1741.51   329.8 1749.36   336.8 1753.58     360 1761.27   422.9 1777.38
   450.6 1785.81   481.3 1793.96   520.2 1805.25   554.6 1812.92   586.5 1818.05
#Mann= 5 ,-1 , 0
       0    .035       0      70     .04       0  199.89      .1       0
   219.2    .045       0   233.4      .1       0
#XS Ineff= 2 , 0
          165.97 1654.02
Permanent Ineff=
       F       F
Bank Sta=219.2,233.4
XS Rating Curve= 0 ,0
Exp/Cntr(USF)=0,0
Exp/Cntr=0.5,0.3

Type RM Length L Ch R = 1 ,6441    ,38.4,38.9,38.7
XS GIS Cut Line= 3
 2064387.4425004271221.0153026122064233.93311158271063.522766757
2064189.12614225271070.276836789
#Sta/Elev= 30
       0 1655.08    19.8 1653.91    42.4 1653.12    56.9 1651.21    65.3 1650.81
    74.5 1649.41    92.8 1648.92   126.5  1647.3     147 1645.69   156.4 1645.76
   175.2 1646.78   184.6 1646.47   189.2 1645.19     194 1642.97   198.7 1641.39
   200.8 1641.49   203.4 1641.14   208.1 1642.17   212.4 1645.47     217 1649.56
   223.5 1655.53   228.2 1660.42   231.5 1664.79   234.8 1671.03   238.1 1677.76
   241.4 1682.45   248.1 1690.56   254.7 1699.15     258 1702.71   265.2 1709.06
#Mann= 5 ,-1 , 0
       0    .035       0      40     .04       0     180      .1       0
     194    .045       0   208.1      .1       0
#XS Ineff= 2 , 0
          179.66    1650  216.22            1650
Permanent Ineff=
       F       F
Bank Sta=194,208.1
XS Rating Curve= 0 ,0
Exp/Cntr(USF)=0,0
Exp/Cntr=0.5,0.3

Type RM Length L Ch R = 1 ,6402    ,159.2,152.3,149.7
XS GIS Cut Line= 5
2064369.03123455271157.9792939942064331.74623096271113.878752119
2064255.17165371271029.285894523 2064226.7067585271034.898690761
2064190.22358295271042.516057085
#Sta/Elev= 30
       0 1651.45     4.5 1651.26    13.1 1650.21    28.8 1648.84    55.2 1648.04
    78.1 1646.64    93.4 1646.07   124.9    1644   131.8 1643.73   137.4 1643.97
   141.31643.404   147.2 1641.72   148.1 1641.85   152.1 1644.44   153.3 1645.01
     157 1645.81   161.8    1646   178.4 1645.99   185.1 1645.46   188.4 1645.95
   191.8 1648.13   198.5  1654.1   205.1 1660.51   208.5 1664.05   211.9 1667.96
   218.6 1680.55   221.9 1685.96   225.1 1689.72     232 1696.76   238.1 1702.14
#Mann= 5 ,-1 , 0
       0    .035       0      10     .04       0   141.3    .045       0
   152.1     .04       0  191.85      .1       0
#XS Ineff= 2 , 0
          137.01    1653  156.91            1653
Permanent Ineff=
       F       F
Bank Sta=141.3,152.1
XS Rating Curve= 0 ,0
Exp/Cntr(USF)=0,0
Exp/Cntr=0.5,0.3

Type RM Length L Ch R = 1 ,6250    ,176.6,177.5,174.5
XS GIS Cut Line= 3
2064469.53271048270958.4900678912064210.75239459270876.219580393
2064145.84281294270939.396593299
#Sta/Elev= 30
       0 1644.11    38.9  1642.9   104.3  1642.5   114.6 1641.88   142.4 1638.15
     149 1637.68   159.4 1637.95     180 1639.38   183.5 1639.34   186.31638.626
   190.3  1637.3   193.8 1637.09   199.21637.565   200.7 1637.85   207.6 1641.96
     211 1643.48   217.9 1645.12   224.8 1645.86     242 1645.52   245.4 1647.11
   255.8 1656.65   262.5 1663.91   266.1 1668.47   269.5 1671.14   272.1 1671.59
   296.3 1681.97   314.6 1687.58   328.4 1689.96   351.3 1692.82   362.1 1694.69
#Mann= 6 ,-1 , 0
       0    .035       0     120      .1       0   186.3    .045       0
   199.2      .1       0     220     .04       0  341.54      .1       0
Bank Sta=186.3,199.2
XS Rating Curve= 0 ,0
Exp/Cntr(USF)=0,0
Exp/Cntr=0.3,0.1

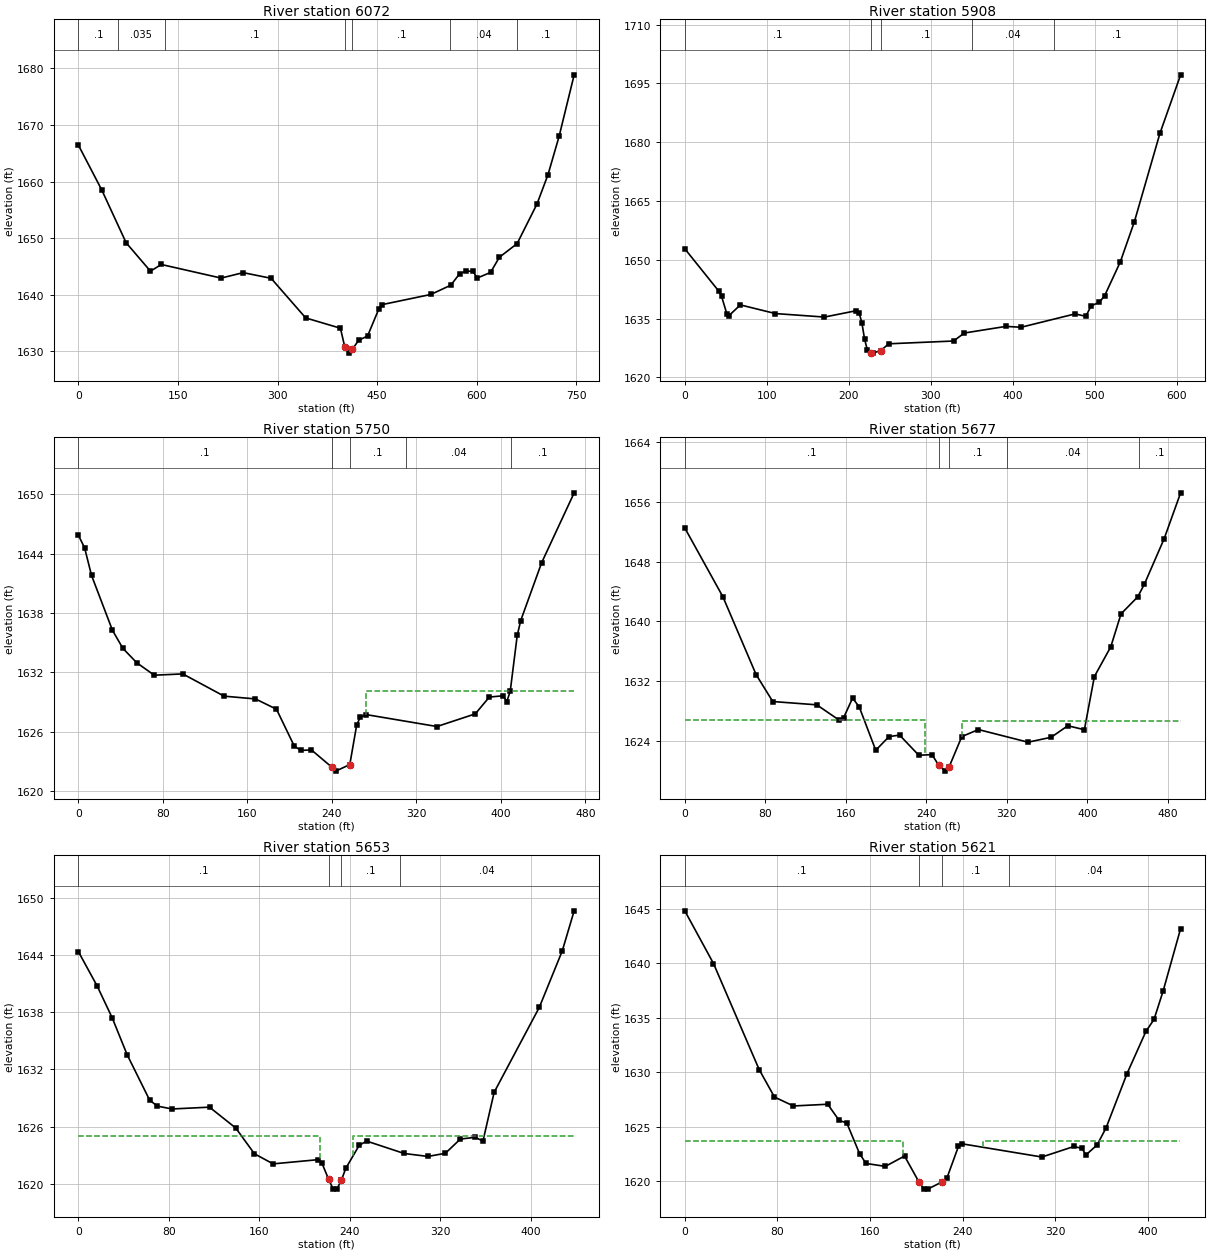
Type RM Length L Ch R = 1 ,6072    ,165.2,164.5,162.6
XS GIS Cut Line= 2
2064808.63546656 270856.61070525 2064072.1056623 270733.65307392
#Sta/Elev= 30
       0 1666.48    35.4 1658.51      72 1649.21   108.6 1644.19     125 1645.37
     215 1642.97   248.3 1643.93   290.3 1642.93   342.4 1635.93   394.7 1634.11
   401.4 1630.73     408 1629.71   412.71630.387   422.1 1631.97   435.6 1632.74
   452.7 1637.56   457.9 1638.29     531 1640.08     561 1641.72   574.3 1643.75
   584.3 1644.22   594.2 1644.14   600.9 1642.98   620.8 1643.97   634.1 1646.65
   660.8 1649.06   690.7 1656.05   707.3 1661.24     724    1668   746.7 1678.88
#Mann= 7 ,-1 , 0
       0      .1       0      60    .035       0     130      .1       0
   401.4    .045       0   412.7      .1       0     560     .04       0
     660      .1       0
Bank Sta=401.4,412.7
XS Rating Curve= 0 ,0
Exp/Cntr(USF)=0,0
Exp/Cntr=0.3,0.1

Type RM Length L Ch R = 1 ,5908    ,155.2,157.6,158.4
XS GIS Cut Line= 2
2064710.02304876 270667.644192032064107.18180681270616.081323267
#Sta/Elev= 30
       0 1652.82    41.5    1642    44.8 1640.73    51.3 1636.22      54 1635.79
    67.8  1638.5   110.6 1636.29   170.4  1635.4   209.4 1637.03   212.9 1636.33
   216.1  1633.9   219.3 1629.85   222.6  1627.1   226.61626.267   229.2  1626.2
   239.11626.847   248.9 1628.58   327.9 1629.29   341.1 1631.33   391.9 1633.02
   410.3  1632.8   476.1  1636.2   489.3  1635.6   495.9 1638.28   505.8 1639.16
   512.3 1640.86   531.4 1649.47   548.6 1659.74   579.7 1682.23     605 1697.19
#Mann= 5 ,-1 , 0
       0      .1       0   226.6    .045       0   239.1      .1       0
     350     .04       0     450      .1       0
#XS Ineff= 1 ,-1
    86.7     206  1630.6
Permanent Ineff=
       F
Bank Sta=226.6,239.1
XS Rating Curve= 0 ,0
Exp/Cntr(USF)=0,0
Exp/Cntr=0.3,0.1

Type RM Length L Ch R = 1 ,5750    ,74,73.3,72.3
XS GIS Cut Line= 2
2064664.69826951270545.5265149572064198.54452939270490.654198854
#Sta/Elev= 30
       0 1645.87     5.9  1644.6    12.5  1641.8    32.3 1636.25    42.2 1634.42
    55.4 1632.96    71.9 1631.71    98.9 1631.84     138 1629.59   167.7 1629.31
   187.6 1628.27   204.4 1624.55   210.7  1624.1   220.6 1624.16   240.2 1622.39
   243.7 1622.01     2571622.674   263.5 1626.66   266.8 1627.45   272.3 1627.73
   339.5 1626.52   375.8  1627.8   389.1  1629.5   402.3 1629.63   405.6 1629.02
   408.9  1630.1   415.5 1635.73   418.8 1637.23   438.6 1643.08   469.4 1650.15
#Mann= 5 ,-1 , 0
       0      .1       0   240.2    .045       0     257      .1       0
     310     .04       0     410      .1       0
#XS Ineff= 2 , 0
                          272.15         1630.13
Permanent Ineff=
       F       F
Bank Sta=240.2,257
XS Rating Curve= 0 ,0
Exp/Cntr(USF)=0,0
Exp/Cntr=0.5,0.3

Type RM Length L Ch R = 1 ,5677    ,24.1,24.1,25.4
XS GIS Cut Line= 4
2064673.51010303270430.0061897082064504.97163073270449.644512461
2064293.82122459270434.5595882072064183.39158958270448.042091763
#Sta/Elev= 30
       0 1652.49    37.9 1643.27    70.9 1632.86    87.4 1629.27   131.1 1628.83
   153.5 1626.77   157.7 1627.08   166.7 1629.73   173.3 1628.55   189.7 1622.75
   202.9 1624.58   213.4 1624.78   232.5 1622.08   245.6 1622.17   252.3 1620.73
   258.8 1619.96   262.5 1620.49   275.2 1624.58   291.7 1625.52     341 1623.83
     364 1624.49   380.5 1626.03     397  1625.5   406.9 1632.61   423.2 1636.59
   433.4    1641   449.9 1643.26   456.5 1644.94   476.2 1651.04   492.6 1657.19
#Mann= 5 ,-1 , 0
       0      .1       0   252.3    .045       0   262.5      .1       0
  319.68     .04       0  451.37      .1       0
#XS Ineff= 2 , 0
          238.59 1626.83  275.21         1626.71
Permanent Ineff=
       F       F
Bank Sta=252.3,262.5
XS Rating Curve= 0 ,0
Exp/Cntr(USF)=0,0
Exp/Cntr=0.5,0.3

Type RM Length L Ch R = 1 ,5653    ,33.6,31.9,32.4
XS GIS Cut Line= 4
2064639.25882745270410.2910818072064496.40918414270429.175326375
2064318.53386051270406.8014926522064205.28083065270424.883909185
#Sta/Elev= 30
       0 1644.37    16.6 1640.76    29.9 1637.42    43.1 1633.55      63 1628.78
    69.8 1628.15    82.8 1627.85   115.9 1628.04   139.1 1625.85   155.6 1623.15
   172.1 1622.09   211.8 1622.53   215.1 1622.21   221.11620.487     225 1619.48
   228.4 1619.44   232.51620.395   236.3 1621.62   248.2 1624.04   254.8 1624.48
   287.9 1623.18   308.9 1622.87   324.3  1623.2   337.5 1624.69   350.8 1624.88
   357.5 1624.47   367.4  1629.6   407.3 1638.51   427.6 1644.44   438.1 1648.64
#Mann= 4 ,-1 , 0
       0      .1       0   221.1    .045       0   232.5      .1       0
  284.09     .04       0
#XS Ineff= 2 ,-1
       0   213.2    1625   242.8   437.9    1625
Permanent Ineff=
       F       F
Bank Sta=221.1,232.5
XS Rating Curve= 0 ,0
Exp/Cntr(USF)=0,0
Exp/Cntr=0.5,0.3

Type RM Length L Ch R = 1 ,5621    ,22.4,23.1,23.9
XS GIS Cut Line= 4
2064637.67265056270389.6707822512064497.61936071270400.659100733
2064304.57550389270368.0987765622064217.01853962270397.284431318
#Sta/Elev= 30
       0 1644.82    24.8 1639.98    64.3 1630.23    77.5 1627.71    93.9 1626.89
   123.5 1627.05   133.4 1625.56     140 1625.33     151 1622.52   156.6 1621.61
   173.3 1621.34   189.9 1622.29   202.5 1619.88   206.5  1619.3   209.9 1619.25
   222.51619.921   226.5 1620.26   236.5 1623.18   239.8 1623.41   308.6  1622.2
   336.3 1623.17   343.2 1622.99   346.7 1622.39   356.3 1623.31     364 1624.86
   382.2 1629.87   398.5 1633.74   405.5 1634.84   413.4 1637.46   428.5 1643.19
#Mann= 4 ,-1 , 0
       0      .1       0   202.5    .045       0   222.5      .1       0
  280.48     .04       0
#XS Ineff= 2 ,-1
       0  188.73 1623.67  258.03     428 1623.71
Permanent Ineff=
       F       F
Bank Sta=202.5,222.5
XS Rating Curve= 0 ,0
Exp/Cntr(USF)=0,0
Exp/Cntr=0.5,0.3

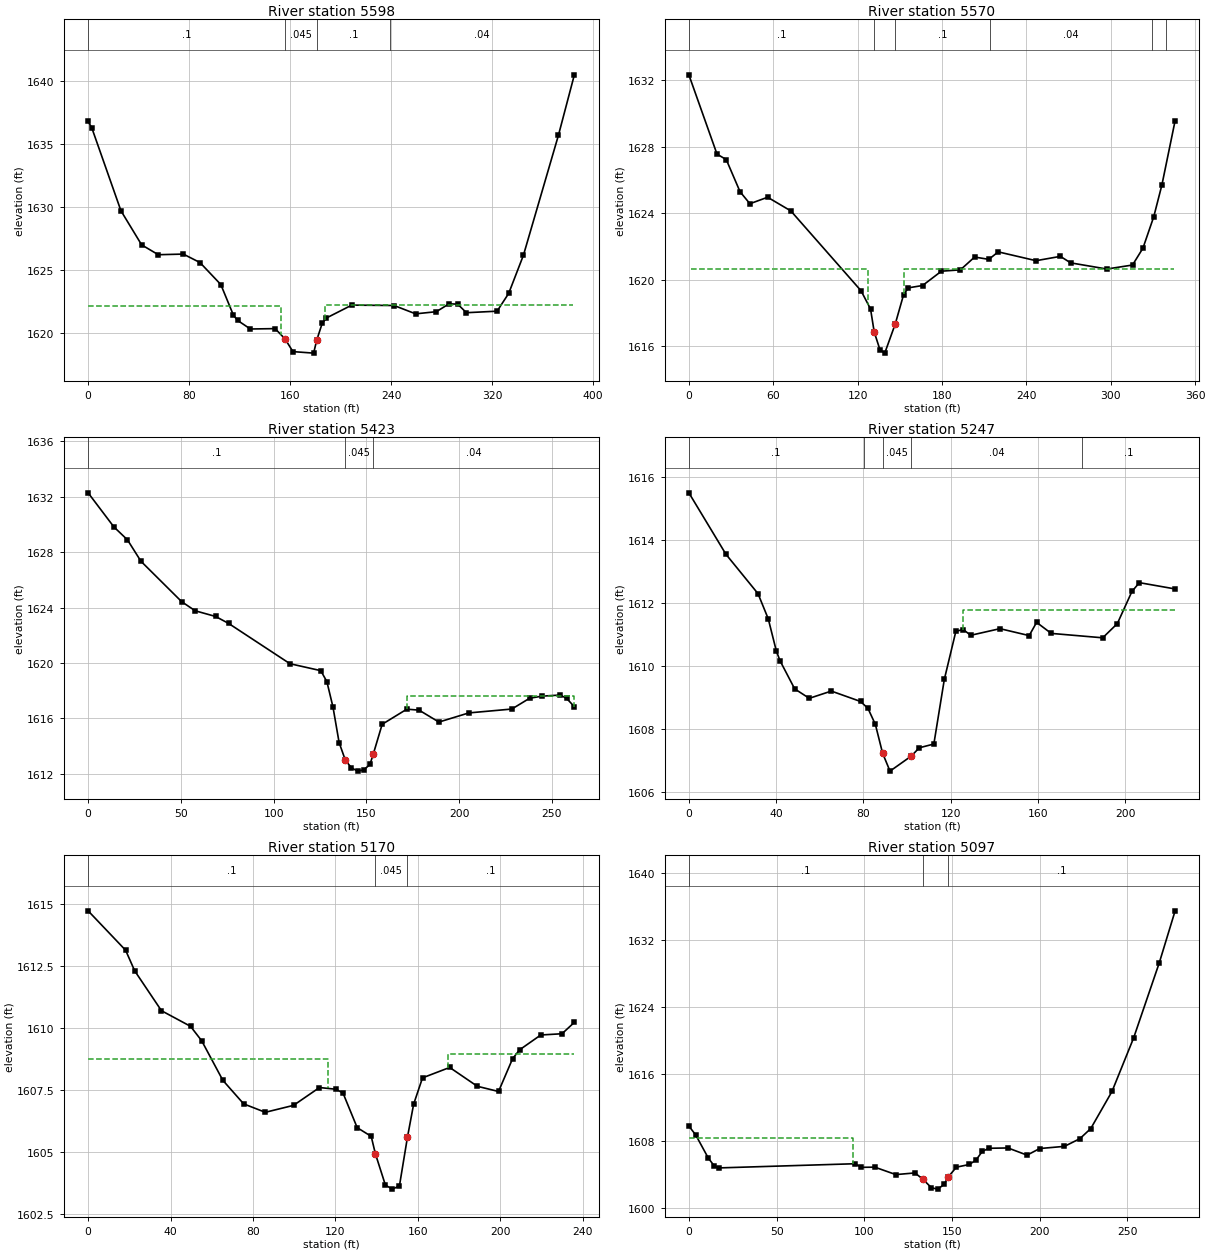
Type RM Length L Ch R = 1 ,5598    ,28.2,28.2,29
XS GIS Cut Line= 4
2064596.11481607270366.8298350512064487.53402808270377.751954073
2064310.92021145270341.7682402072064220.50812878270373.174542607
#Sta/Elev= 30
       0 1636.78     2.9 1636.28      26 1629.71    42.4 1627.01    55.6 1626.23
    75.4 1626.28    88.6 1625.61   105.1 1623.87   115.1 1621.44   118.4 1621.03
   128.5 1620.35   148.1 1620.38   155.91619.574   162.2 1618.56   178.6 1618.44
   181.1 1619.48   185.4  1620.8   188.7 1621.22   208.8 1622.24   242.3 1622.21
   259.4 1621.55   275.8 1621.72   285.8 1622.34   292.7 1622.32   299.6 1621.64
   323.9 1621.76   333.1 1623.17   344.8  1626.2   372.5 1635.69   385.1 1640.47
#Mann= 4 ,-1 , 0
       0      .1       0   155.9    .045       0   181.1      .1       0
  239.13     .04       0
#XS Ineff= 2 ,-1
       0  153.01 1622.16  187.49   384.2 1622.27
Permanent Ineff=
       F       F
Bank Sta=155.9,181.1
XS Rating Curve= 0 ,0
Exp/Cntr(USF)=0,0
Exp/Cntr=0.5,0.3

Type RM Length L Ch R = 1 ,5570    ,151.4,146.9,142.2
XS GIS Cut Line= 4
2064573.88010072270345.835384751 2064479.4492681270348.446375514
2064318.87333614270311.8925048242064241.41394349270350.622201151
#Sta/Elev= 30
       0 1632.31      20 1627.55    26.6 1627.22    36.4 1625.29    43.4 1624.57
      56 1624.96    72.5 1624.14   122.4 1619.35   129.2 1618.25   131.8 1616.87
   135.9  1615.8   139.3  1615.6   146.8 1617.36   152.7 1619.11   156.1 1619.52
   166.2 1619.66   179.6 1620.52   193.1  1620.6   203.2 1621.37   213.3 1621.23
     220 1621.68   246.9 1621.15   264.2 1621.41   271.5 1621.02   297.2 1620.65
   315.5 1620.89   322.9  1621.9   330.6 1623.79   336.4  1625.7   345.8 1629.56
#Mann= 6 ,-1 , 0
       0      .1       0   131.8    .045       0   146.8      .1       0
  214.47     .04       0  329.15      .1       0  339.15     .04       0
#XS Ineff= 2 ,-1
    1.38  127.581620.661  153.21  345.161620.661
Permanent Ineff=
       F       F
Bank Sta=131.8,146.8
XS Rating Curve= 0 ,0
Exp/Cntr(USF)=0,0
Exp/Cntr=0.5,0.3

Type RM Length L Ch R = 1 ,5423    ,176.2,175.8,174.5
XS GIS Cut Line= 3
2064589.37059704270215.8995901532064524.21833193270184.134264763
2064336.49592573270210.844579239
#Sta/Elev= 30
       0 1632.28    13.9 1629.82    21.2 1628.89    28.5 1627.34    50.4 1624.43
    57.7 1623.77    68.7 1623.36    75.7 1622.86   108.8 1619.95   125.4 1619.45
   128.7 1618.66     132 1616.82   135.3 1614.26   138.6 1613.01   141.9 1612.44
   145.3  1612.2   148.6 1612.29   151.9 1612.68   153.71613.422   158.5 1615.58
   171.8 1616.67   178.4  1616.6   189.1 1615.74   205.2  1616.4   228.4 1616.68
     238 1617.46   244.7 1617.61   254.5 1617.69   257.9 1617.45   262.1 1616.85
#Mann= 3 ,-1 , 0
       0      .1       0   138.6    .045       0   153.7     .04       0
#XS Ineff= 2 , 0
                          172.06         1617.63
Permanent Ineff=
       F       F
Bank Sta=138.6,153.7
XS Rating Curve= 0 ,0
Exp/Cntr(USF)=0,0
Exp/Cntr=0.3,0.1

Type RM Length L Ch R = 1 ,5247    ,71,77.6,83.2
XS GIS Cut Line= 3
2064520.72426053270041.6082619342064493.19037178270012.485879601
2064314.74959276270052.198219146
#Sta/Elev= 30
       0 1615.49      17 1613.54    31.7 1612.29    36.4 1611.49    40.1 1610.47
    41.8 1610.16    48.5 1609.27    55.2 1608.97    65.3  1609.2    78.7 1608.87
    82.1 1608.65    85.5 1608.14    88.8 1607.23    92.2 1606.66     102 1607.14
   105.6  1607.4   112.3 1607.52   117.1 1609.57   122.4  1611.1   125.8 1611.15
   129.2 1610.97   142.6 1611.18     156 1610.96   159.4 1611.38   166.1 1611.03
   189.7 1610.89   196.4 1611.34   203.1 1612.36   206.5 1612.64   222.9 1612.44
#Mann= 5 ,-1 , 0
       0      .1       0   80.08     .04       0    88.8    .045       0
     102     .04       0  180.08      .1       0
#XS Ineff= 2 , 0
                          125.77         1611.78
Permanent Ineff=
       F       F
Bank Sta=88.8,102
XS Rating Curve= 0 ,0
Exp/Cntr(USF)=0,0
Exp/Cntr=0.3,0.1

Type RM Length L Ch R = 1 ,5170    ,71.2,72.7,75
XS GIS Cut Line= 3
2064574.21631737270016.6998800612064539.12019024269976.454015981
2064364.42033223269923.350564484
#Sta/Elev= 30
       0 1614.73    18.2 1613.14    22.6 1612.31    35.6  1610.7    49.7 1610.07
    55.1 1609.49    65.4 1607.89    75.5 1606.94      86  1606.6    99.7 1606.88
   112.3  1607.6   120.3 1607.53   123.7 1607.38   130.6 1605.98   137.4 1605.63
   139.41604.935   144.3 1603.66   147.7  1603.5   151.1 1603.63     1551605.599
     158 1606.93   162.3 1607.99   175.5 1608.41   188.9 1607.65   199.2 1607.44
     206 1608.76   209.4 1609.12   219.7 1609.72     230 1609.77     236 1610.23
#Mann= 3 ,-1 , 0
       0      .1       0   139.4    .045       0     155      .1       0
#XS Ineff= 2 , 0
           116.2 1608.77  174.51         1608.95
Permanent Ineff=
       F       F
Bank Sta=139.4,155
XS Rating Curve= 0 ,0
Exp/Cntr(USF)=0,0
Exp/Cntr=0.3,0.1

Type RM Length L Ch R = 1 ,5097    ,116.2,119.8,122.9
XS GIS Cut Line= 2
2064606.59774914269943.4877914212064356.21664929269824.524558734
#Sta/Elev= 30
       0 1609.75     3.9 1608.69    11.1 1605.91    14.6 1604.94    17.1 1604.74
    94.7 1605.24    98.4 1604.81     106 1604.83     118 1603.94   128.9 1604.14
   133.51603.368   138.3 1602.36   141.9  1602.2   145.5 1602.77   147.81603.644
   152.5 1604.83   159.9 1605.15   163.7 1605.69   167.3 1606.72     171 1607.09
   181.9 1607.13   192.8 1606.27     200 1607.06   214.1 1607.32   222.9 1608.24
   229.1 1609.45   241.2 1613.89   253.5 1620.28   268.2 1629.32   277.2 1635.52
#Mann= 3 , 0 , 0
       0      .1       0   133.5    .045       0   147.8      .1       0
#XS Ineff= 2 , 0
           93.35 1608.27
Permanent Ineff=
       F       F
Bank Sta=133.5,147.8
XS Rating Curve= 0 ,0
Exp/Cntr(USF)=0,0
Exp/Cntr=0.3,0.1