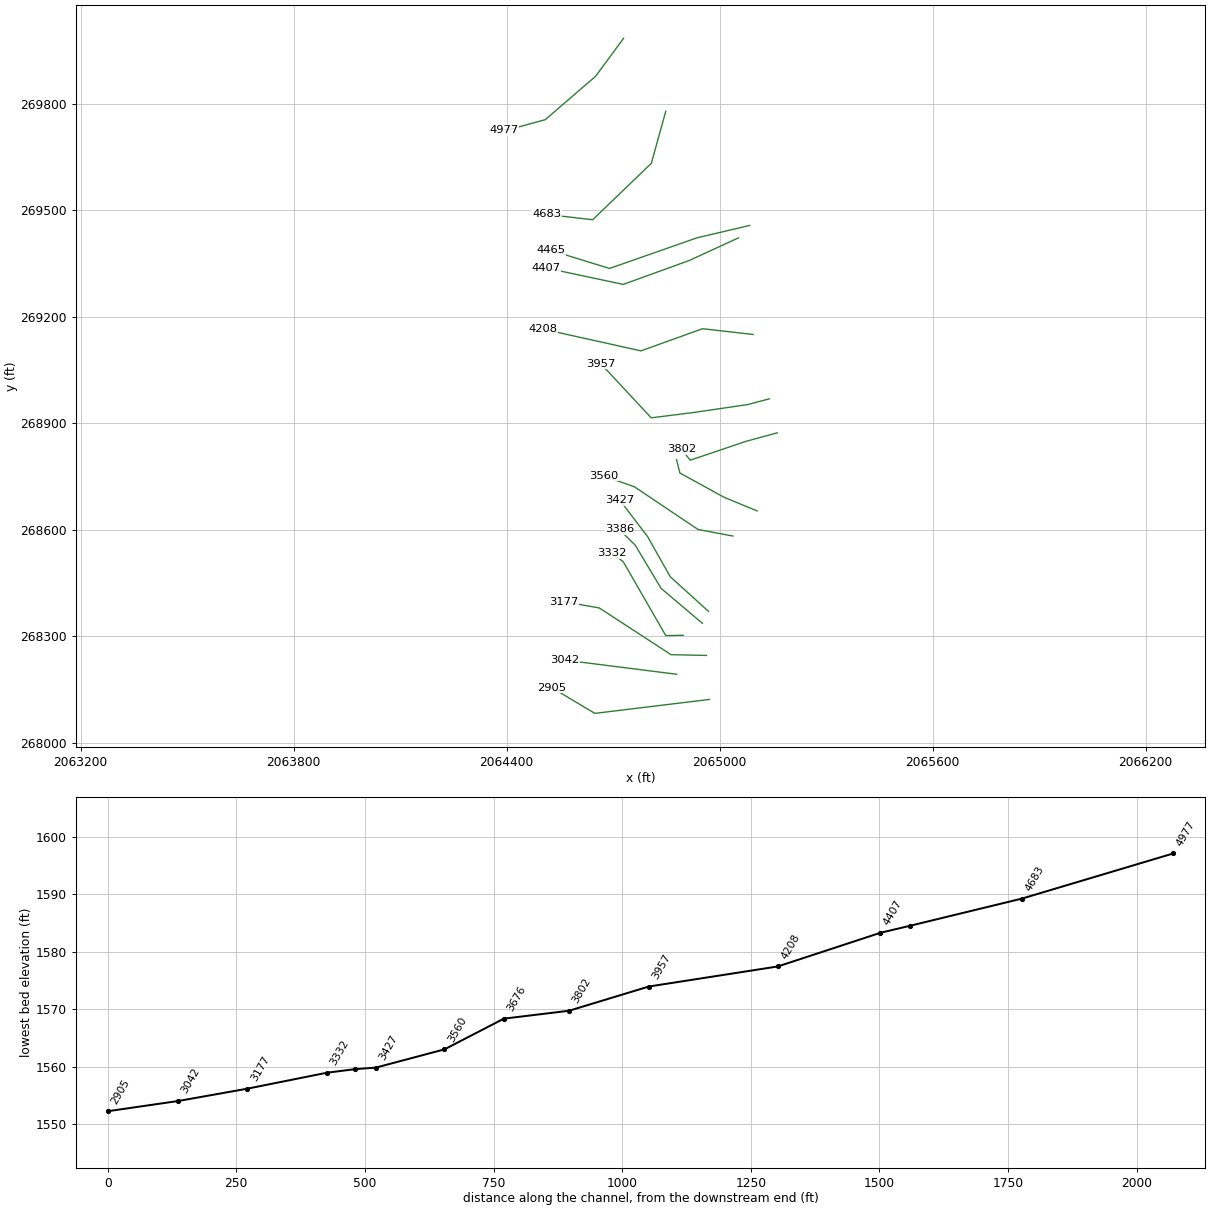
HEC-RAS study GREENBRRV_T1.prj: GREENBRRV_T1

--- GREENBRRV_T1.g01 (geometry) --- (continued)

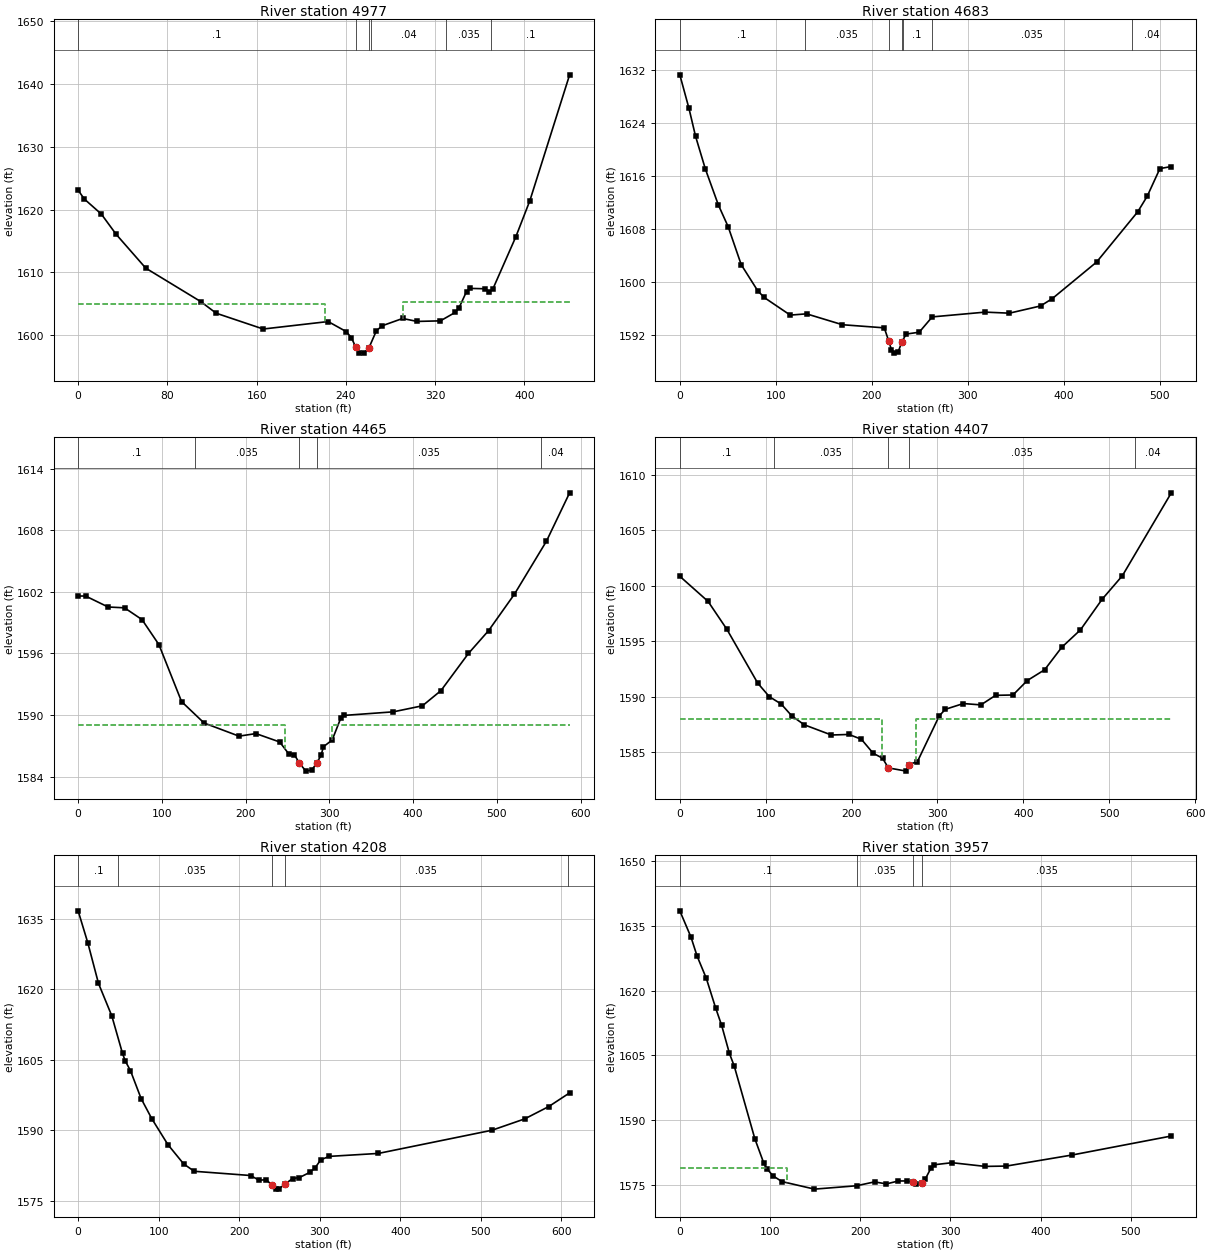
Type RM Length L Ch R = 1 ,4977    ,293.5,294.4,294.8
XS GIS Cut Line= 5
2064729.33689017269984.4948554132064650.61205097269877.596522396
2064508.78618573269755.3463946032064410.81104824269728.596002177
2064392.03071729269726.150286362
#Sta/Elev= 30
       0 1623.08     5.6 1621.67    20.8 1619.28    34.1 1616.05    60.6 1610.67
   109.9 1605.34   123.7 1603.49   165.9 1600.97   224.1 1602.16   240.4 1600.55
     245 1599.56   248.9 1598.05     252  1597.2   256.1 1597.13   260.5 1597.91
   267.3 1600.68   272.4 1601.48   290.8 1602.65   303.8 1602.18   324.7 1602.27
   337.9 1603.61   341.3 1604.32   348.1 1606.93   351.5 1607.44   365.1 1607.38
   368.5 1606.86   371.9 1607.42   392.3 1615.66   404.9 1621.43   440.5 1641.46
#Mann= 6 ,-1 , 0
       0      .1       0   248.9    .045       0   260.5      .1       0
  262.76     .04       0     330    .035       0     370      .1       0
#XS Ineff= 2 , 0
          220.85    1605  291.55         1605.23
Permanent Ineff=
       F       F
Bank Sta=248.9,260.5
XS Rating Curve= 0 ,0
Exp/Cntr(USF)=0,0
Exp/Cntr=0.3,0.1

Type RM Length L Ch R = 1 ,4683    ,221.9,218,212.8
XS GIS Cut Line= 4
2064848.28241008 269779.266981232064807.53497058269632.347684381
2064642.35557967269473.4968391162064512.55927445269488.473335873
#Sta/Elev= 30
       0 1631.21     9.5 1626.17    16.4 1621.95    26.6 1617.03    40.2 1611.59
    50.4 1608.32      64  1602.6    81.1 1598.69    87.9 1597.66   115.1    1595
   132.1 1595.19   169.5 1593.55   213.1 1593.08   217.6 1591.16   220.6 1589.77
   223.6 1589.27   227.5 1589.44   231.3 1590.88   235.8 1592.14   249.5 1592.42
   263.1 1594.73   318.3 1595.45   343.5 1595.29     376 1596.38   388.1 1597.47
   434.4 1602.99   477.3 1610.57   487.2 1612.92   500.4 1617.08   512.3 1617.39
#Mann= 7 ,-1 , 0
       0      .1       0     130    .035       0   217.6    .045       0
   231.3    .035       0  232.47      .1       0  262.47    .035       0
  471.63     .04       0
Bank Sta=217.6,231.3
XS Rating Curve= 0 ,0
Exp/Cntr(USF)=0,0
Exp/Cntr=0.5,0.3

Type RM Length L Ch R = 1 ,4465    ,57.7,57.1,59.2
XS GIS Cut Line= 4
2065084.16223399269457.2723009632064935.64530782269422.327141864
2064689.78115274269336.2122855142064523.79164702269387.381982765
#Sta/Elev= 30
       0  1601.6     8.9  1601.6    35.8 1600.53    55.4 1600.45    76.3  1599.3
    96.5 1596.86   123.5 1591.31   150.4 1589.22   192.1 1587.94   212.3 1588.19
   240.7 1587.37   251.2 1586.24   258.1 1586.15   264.3 1585.29     272 1584.53
     279 1584.64   284.8 1585.31     290 1586.06   292.9 1586.91   303.3 1587.56
   313.7 1589.72   317.2 1589.96   376.3 1590.31   411.1  1590.9   433.2 1592.38
     466    1596   490.1 1598.23     521 1601.79   559.1 1606.94   586.8 1611.66
#Mann= 5 ,-1 , 0
       0      .1       0     140    .035       0   264.3    .045       0
   284.8    .035       0  553.08     .04       0
#XS Ineff= 2 ,-1
       0     247    1589     303 586.779    1589
Permanent Ineff=
       F       F
Bank Sta=264.3,284.8
XS Rating Curve= 0 ,0
Exp/Cntr(USF)=0,0
Exp/Cntr=0.5,0.3

Type RM Length L Ch R = 1 ,4407    ,199.5,199.5,197.6
XS GIS Cut Line= 4
2065052.96119908269422.3271418642064914.42860408269358.677030649
2064728.47043602269291.2827952442064511.31123305 269337.46032691
#Sta/Elev= 30
       0 1600.85    32.9 1598.59    54.8 1596.08    90.7 1591.24   104.2 1590.02
     118 1589.36   130.4 1588.29   144.9 1587.49   176.5 1586.57   196.9 1586.62
   211.4 1586.19   225.1 1584.93   236.1 1584.48   242.8 1583.61   263.8 1583.32
   266.5 1583.91   276.7 1584.18   302.1 1588.29   309.1 1588.88   330.1  1589.4
   350.6 1589.28   367.7 1590.14   387.9 1590.17   404.6 1591.47   424.8 1592.44
   444.7 1594.46   466.5 1596.03   491.8 1598.79   515.3  1600.9   572.3 1608.36
#Mann= 5 ,-1 , 0
       0      .1       0     110    .035       0   242.8    .045       0
   266.5    .035       0  530.25     .04       0
#XS Ineff= 2 , 0
           235.5    1588   274.7            1588
Permanent Ineff=
       F       F
Bank Sta=242.8,266.5
XS Rating Curve= 0 ,0
Exp/Cntr(USF)=0,0
Exp/Cntr=0.5,0.3

Type RM Length L Ch R = 1 ,4208    ,251.7,250.6,245.3
XS GIS Cut Line= 4
2065094.14656516269150.2541174522064951.86984598269166.478655605
2064778.39209188269104.0765857862064502.57494328269165.230614209
#Sta/Elev= 30
       0 1636.71    12.1 1629.86    25.3 1621.25    41.8 1614.35    55.1 1606.36
    58.4 1604.79      65 1602.67    78.2 1596.74    91.4 1592.47   111.4 1586.95
     131 1582.83   144.1 1581.26     214 1580.36   224.5 1579.37   233.8 1579.45
   240.5  1578.3   245.4 1577.48   248.9 1577.46   256.9 1578.54   266.3 1579.72
   274.8 1579.93   287.7 1581.04   294.2 1582.01   301.2  1583.7   311.6 1584.43
   372.7 1585.06   513.8    1590   554.3 1592.41   584.2 1595.04   610.1 1597.95
#Mann= 5 ,-1 , 0
       0      .1       0      50    .035       0   240.5    .045       0
   256.9    .035       0  607.56     .06       0
Bank Sta=240.5,256.9
XS Rating Curve= 0 ,0
Exp/Cntr(USF)=0,0
Exp/Cntr=0.3,0.1

Type RM Length L Ch R = 1 ,3957    ,152.3,155.4,157.4
XS GIS Cut Line= 5
2065140.04700647 268968.90904237 2065078.6121383268952.668184137
2064925.85625961268930.2974141872064807.25057672268915.433752134
2064665.81114995269067.349227136
#Sta/Elev= 30
       0 1638.52    12.4 1632.41    19.2    1628    29.4 1622.85    39.6 1616.07
    46.4 1611.94      55 1605.45    60.3 1602.54    83.2 1585.65    93.2 1579.94
    96.5 1578.74   103.1 1577.09   113.1 1575.73   149.3 1573.97     196 1574.75
   215.9 1575.65   229.1 1575.18   242.3 1575.86   252.2 1575.87   258.81575.508
   262.2 1575.14   268.3 1575.45   272.1 1576.28   278.7 1578.93     282 1579.62
   301.8  1580.1   338.6 1579.24   362.1 1579.32   434.9 1581.88     545 1586.29
#Mann= 4 ,-1 , 0
       0      .1       0     196    .035       0   258.8    .045       0
   268.3    .035       0
#XS Ineff= 2 , 0
          118.35 1578.82
Permanent Ineff=
       F       F
Bank Sta=258.8,268.3
XS Rating Curve= 0 ,0
Exp/Cntr(USF)=0,0
Exp/Cntr=0.3,0.1

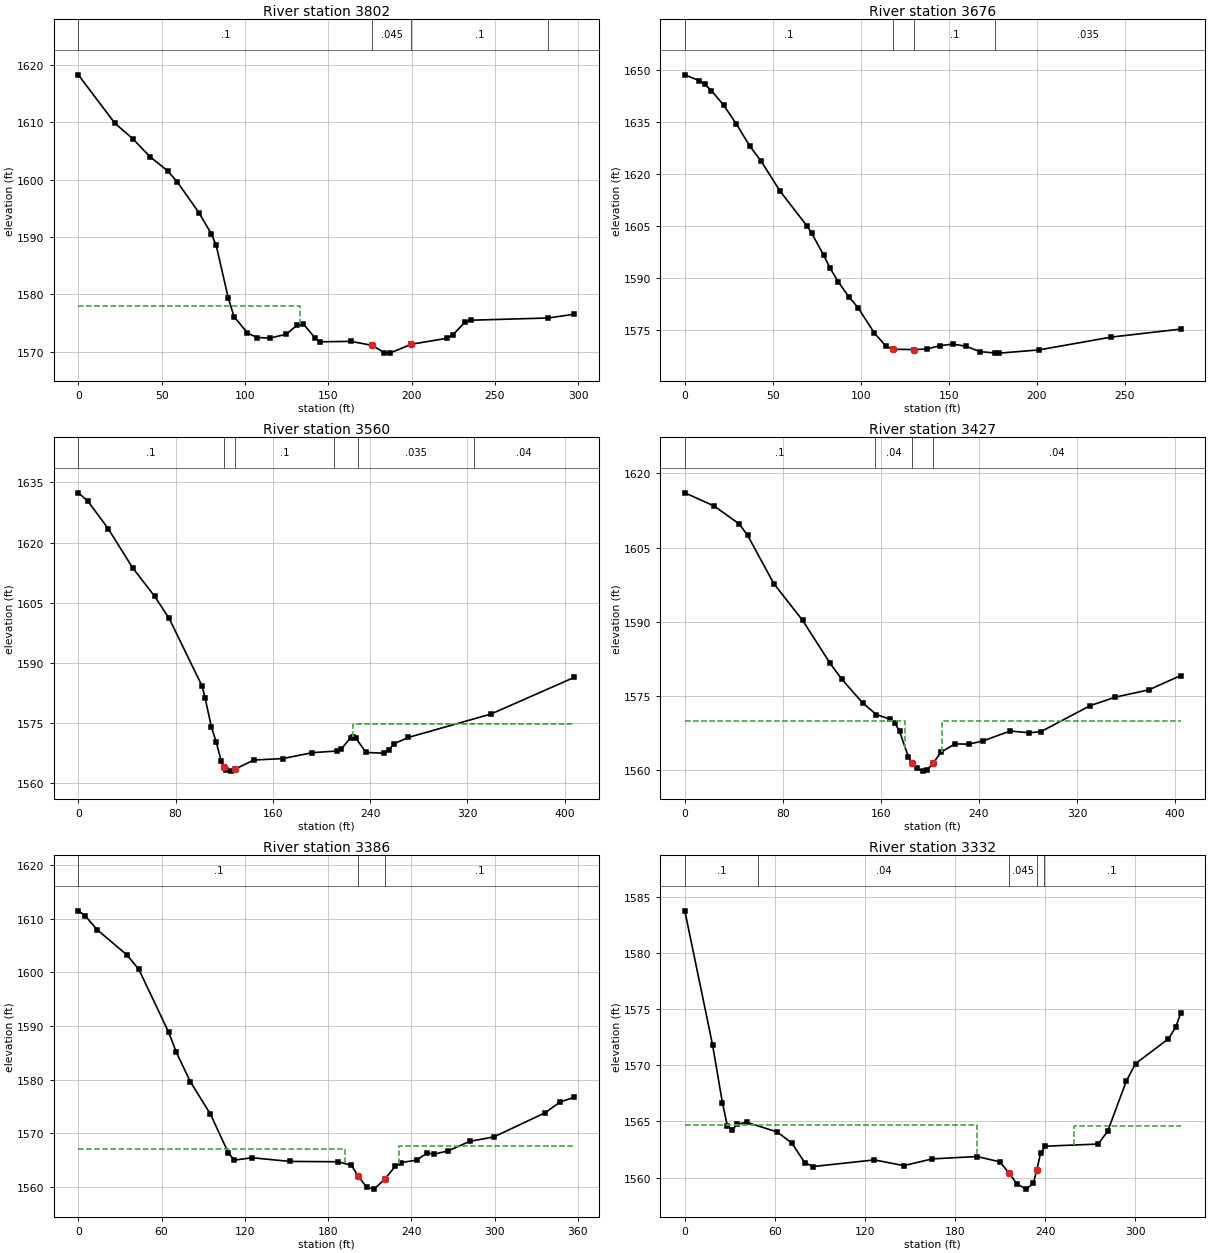
Type RM Length L Ch R = 1 ,3802    ,136.4,126.4,118.6
XS GIS Cut Line= 4
2065162.32130108268873.1270371672065072.89640742268848.775239549
2064917.16574072268796.0561558132064891.99262195268827.682211633
#Sta/Elev= 30
       0 1618.31    21.9 1609.87    32.7 1607.14      43 1604.02    53.6 1601.55
    59.3 1599.65    72.4 1594.23    79.7 1590.62    82.7 1588.57    89.9 1579.44
    93.4 1576.13   101.5 1573.26   107.2 1572.47   115.2 1572.39   124.8 1573.05
   131.5 1574.69   134.9 1574.88   141.9 1572.44   145.3 1571.73   163.6  1571.8
   176.5 1571.09   183.4 1569.83   186.9 1569.75   199.8  1571.3   221.5 1572.36
     225    1573   231.9 1575.16   235.4 1575.49   281.8 1575.88   297.5 1576.53
#Mann= 4 ,-1 , 0
       0      .1       0   176.5    .045       0   199.8      .1       0
   281.8    .035       0
#XS Ineff= 2 , 0
          132.91 1577.95
Permanent Ineff=
       F       F
Bank Sta=176.5,199.8
XS Rating Curve= 0 ,0
Exp/Cntr(USF)=0,0
Exp/Cntr=0.3,0.1

Type RM Length L Ch R = 1 ,3676    ,117.1,115.7,114.9
XS GIS Cut Line= 4
2065105.85408455268653.0504356412065012.47239188268691.642511038
2064888.04039464268759.9477350552064878.63272663268797.550806042
#Sta/Elev= 30
       0 1648.69       8 1647.05    11.5  1645.9    15.1 1644.14    22.2 1639.86
    29.3 1634.52    36.9 1628.16    43.5 1623.69    54.1 1615.15    69.6 1604.98
    72.1    1603      79  1596.6    82.5 1592.93    87.2 1588.98    93.2 1584.63
    98.4 1581.54   107.7 1574.22   114.3  1570.4   118.41569.485   130.21569.416
   137.6 1569.56   145.1 1570.55   152.6 1570.98   160.1 1570.33   167.6 1568.83
   176.4 1568.41   178.8 1568.38   201.3 1569.31   242.3    1573   281.8 1575.31
#Mann= 4 ,-1 , 0
       0      .1       0   118.4    .045       0   130.2      .1       0
   176.4    .035       0
Bank Sta=118.4,130.2
XS Rating Curve= 0 ,0
Exp/Cntr(USF)=0,0
Exp/Cntr=0.3,0.1

Type RM Length L Ch R = 1 ,3560    ,139.3,133.3,127.1
XS GIS Cut Line= 4
2065037.36591906268582.3568416652064939.05714939268600.983766444
2064760.03170568268721.023948357 2064673.1060567 268752.06882299
#Sta/Elev= 30
       0  1632.4     7.9  1630.3    24.6 1623.46    44.6 1613.75    62.8  1606.6
    74.7 1601.11   101.8 1584.23   104.2 1581.38   109.5 1573.98   113.5 1570.25
   117.4 1565.66   119.7 1564.01   121.4 1563.24   125.3 1563.03   129.11563.551
   144.4  1565.8     168 1566.15   192.5 1567.63   212.9 1568.05   216.2 1568.51
   224.1 1571.39   225.7  1571.5   228.1 1571.36   236.6 1567.69   251.8 1567.49
   255.2 1568.23   259.7 1569.86   271.5 1571.43   339.4 1577.25   407.9 1586.39
#Mann= 6 ,-1 , 0
       0      .1       0   119.7    .045       0   129.1      .1       0
  210.06     .04       0  230.06    .035       0   325.6     .04       0
#XS Ineff= 2 , 0
                           226.2         1574.67
Permanent Ineff=
       F       F
Bank Sta=119.7,129.1
XS Rating Curve= 0 ,0
Exp/Cntr(USF)=0,0
Exp/Cntr=0.5,0.3

Type RM Length L Ch R = 1 ,3427    ,40.2,40.3,40.7
XS GIS Cut Line= 4
2064968.61502993268370.2613217692064860.91470334268467.681479245
2064797.17109769268580.6716055632064718.58444144268683.803581444
#Sta/Elev= 30
       0 1616.06    23.9  1613.4    44.3  1609.8    51.3 1607.45    72.6 1597.74
    96.1 1590.32   118.6 1581.63   127.9 1578.49   145.2 1573.61   156.4 1571.27
   167.7 1570.34   171.4 1569.58   175.2  1567.9   182.5 1562.72   185.21561.582
   189.2 1560.41     194 1559.86   197.8 1560.12   202.81561.527   209.1 1563.67
   220.4 1565.36   231.7  1565.3     243 1565.93   265.6 1567.97   281.2  1567.6
   290.6 1567.83   330.7 1573.07   351.4 1574.81   378.6 1576.27   404.6 1579.15
#Mann= 4 ,-1 , 0
       0      .1       0  155.22     .04       0   185.2    .045       0
   202.8     .04       0
#XS Ineff= 2 , 0
             180    1570     210            1570
Permanent Ineff=
       F       F
Bank Sta=185.2,202.8
XS Rating Curve= 0 ,0
Exp/Cntr(USF)=0,0
Exp/Cntr=0.5,0.3

Type RM Length L Ch R = 1 ,3386    ,54.4,54.2,54
XS GIS Cut Line= 4
2064951.31806288268336.5957068212064835.10538481268435.016206688
2064762.37286789 268556.426905572064717.15569833268601.142169745
#Sta/Elev= 30
       0 1611.49     4.9 1610.59    13.5 1607.98      35 1603.27    43.6 1600.57
    65.1 1588.86    70.6 1585.13    80.8 1579.59    95.2 1573.59   108.1 1566.38
   112.4    1565   125.3 1565.44   152.3 1564.76   187.3 1564.69   196.9 1564.01
   201.81561.995   207.9 1559.92   213.2 1559.59   220.91561.459   228.5 1563.86
   232.3 1564.52   243.8    1565   251.4 1566.32   256.7 1566.13   266.7 1566.73
     282 1568.49   299.5 1569.33   336.6 1573.84   347.1 1575.82   357.4 1576.71
#Mann= 3 , 0 , 0
       0      .1       0   201.8    .045       0   220.9      .1       0
#XS Ineff= 2 , 0
          191.98 1567.09  231.22         1567.64
Permanent Ineff=
       F       F
Bank Sta=201.8,220.9
XS Rating Curve= 0 ,0
Exp/Cntr(USF)=0,0
Exp/Cntr=0.3,0.1

Type RM Length L Ch R = 1 ,3332    ,144,155.4,158.5
XS GIS Cut Line= 4
2064897.20878775268302.8240128982064848.23065759268301.941504645
2064728.45514663268510.1227456072064695.61163363268534.785512455
#Sta/Elev= 30
       0 1583.74    18.5  1571.8    25.1 1566.63    28.4 1564.58    31.7 1564.26
    34.9 1564.77    41.5 1564.91    61.5 1564.07    71.1  1563.1      80 1561.32
    85.5 1560.99   126.3 1561.58   145.8 1561.07   164.8 1561.67   194.6 1561.88
   209.8 1561.41   216.11560.388   221.1 1559.45   227.3 1558.98   232.1 1559.49
   234.41560.694   236.9 1562.15   240.1  1562.8   275.3 1562.99   281.7 1564.15
   294.1 1568.62   300.2 1570.15   322.1 1572.35     327  1573.4   330.2 1574.64
#Mann= 5 ,-1 , 0
       0      .1       0   48.99     .04       0   216.1    .045       0
   234.4     .04       0  238.99      .1       0
#XS Ineff= 2 , 0
          194.82 1564.69   259.1         1564.57
Permanent Ineff=
       F       F
Bank Sta=216.1,234.4
XS Rating Curve= 0 ,0
Exp/Cntr(USF)=0,0
Exp/Cntr=0.3,0.1

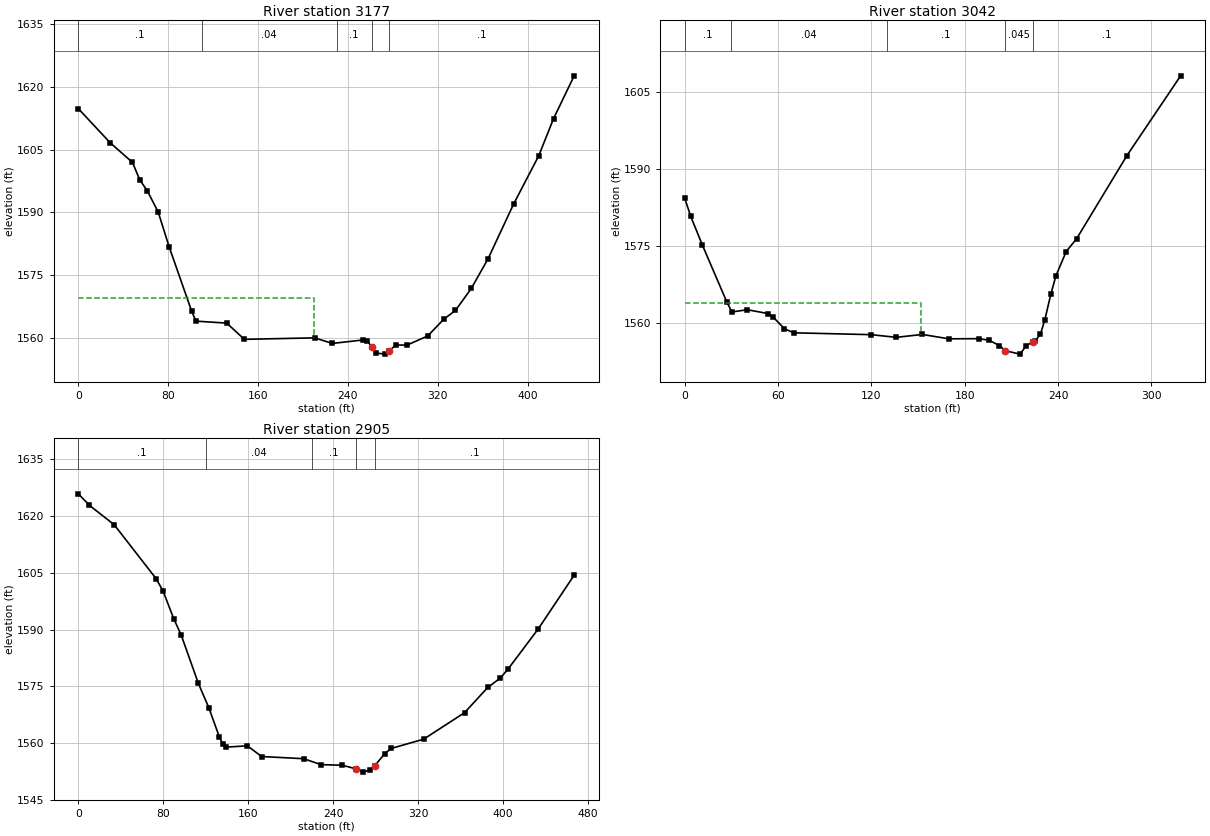
Type RM Length L Ch R = 1 ,3177    ,127.9,134.2,140.5
XS GIS Cut Line= 4
2064962.92734998 268245.999205312064863.09956932268248.237864137
2064660.76485362268379.8658746442064562.06391616268397.207068265
#Sta/Elev= 30
       0 1614.75    28.5 1606.57    48.2 1601.93    54.7 1597.75    61.3  1595.2
    71.1 1590.08    80.9 1581.74   100.8  1566.5   104.7 1564.06   132.1 1563.59
   147.8 1559.72   210.4 1560.07   226.1 1558.74   253.5 1559.57   257.4 1559.37
   261.2 1557.81   265.2 1556.45     273 1556.19   276.31556.887   282.7 1558.36
   292.6 1558.34   311.1 1560.54   325.4 1564.54   335.7  1566.6   349.8 1571.85
   364.8 1578.96   387.4 1591.94   409.8 1603.47   423.1  1612.4   441.4 1622.58
#Mann= 5 ,-1 , 0
       0      .1       0  109.85     .04       0  229.85      .1       0
   261.2    .045       0   276.3      .1       0
#XS Ineff= 2 , 0
          210.12 1569.57
Permanent Ineff=
       F       F
Bank Sta=261.2,276.3
XS Rating Curve= 0 ,0
Exp/Cntr(USF)=0,0
Exp/Cntr=0.3,0.1

Type RM Length L Ch R = 1 ,3042    ,134.5,137.1,141.1
XS GIS Cut Line= 2
2064879.21642902268193.0175829782064562.92588944 268232.94440448
#Sta/Elev= 30
       0 1584.27     3.8  1580.8    11.3 1575.22      27 1564.18    30.3 1562.23
    40.2 1562.67    53.4 1561.93    56.8 1561.24    64.1 1558.97      70 1558.19
   119.6 1557.83   136.1 1557.31   152.7 1557.87   169.8 1557.02     189 1557.05
   195.6 1556.75   202.3 1555.71   206.21554.702   215.5 1554.05   219.7 1555.72
   224.11556.486   225.4 1556.62   228.7 1557.96   231.5 1560.72   235.3 1565.64
   238.6 1569.23   245.2 1573.95   251.9 1576.44   284.3  1592.6   318.8 1608.07
#Mann= 5 ,-1 , 0
       0      .1       0      30     .04       0     130      .1       0
   206.2    .045       0   224.1      .1       0
#XS Ineff= 2 , 0
          151.71 1564.04
Permanent Ineff=
       F       F
Bank Sta=206.2,224.1
XS Rating Curve= 0 ,0
Exp/Cntr(USF)=0,0
Exp/Cntr=0.3,0.1

Type RM Length L Ch R = 1 ,2905    ,276.2,269,256.1
XS GIS Cut Line= 3
2064971.14444374 268122.076100032064648.45612265268082.823896661
2064526.72036376268155.502397343
#Sta/Elev= 30
       0 1625.91    10.5 1622.85    33.7 1617.75    73.3 1603.44    79.9  1600.1
    89.8 1592.88    96.9  1588.5     113 1575.75   122.9 1569.28   132.8 1561.55
   136.1 1559.64   139.4 1558.89   159.2 1559.23   172.5  1556.4   212.1 1555.82
   228.6 1554.25   248.5 1554.09   261.21553.156   268.3 1552.27   274.9 1552.89
   279.11553.962   288.4 1557.16   294.7 1558.55   325.1 1560.99   363.6    1568
   385.5 1574.69   397.1 1577.12   404.6 1579.55     433 1590.17   466.8 1604.38
#Mann= 5 ,-1 , 0
       0      .1       0     120     .04       0     220      .1       0
   261.2    .045       0   279.1      .1       0
Bank Sta=261.2,279.1
XS Rating Curve= 0 ,0
Exp/Cntr(USF)=0,0
Exp/Cntr=0.3,0.1