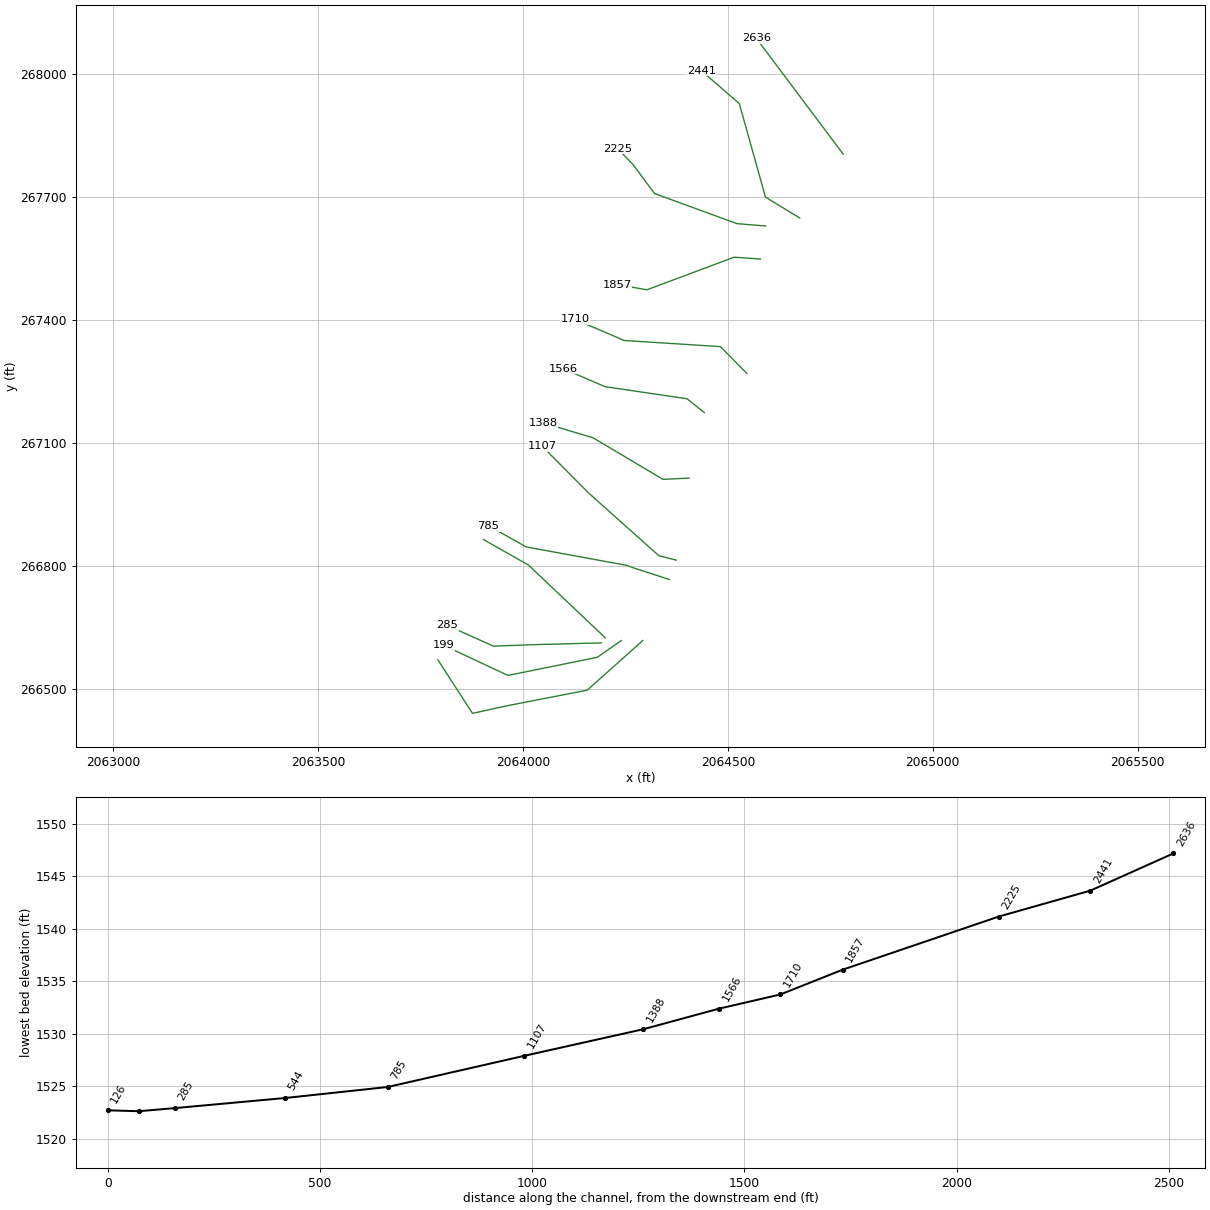
HEC-RAS study GREENBRRV_T1.prj: GREENBRRV_T1

--- GREENBRRV_T1.g01 (geometry) --- (continued)

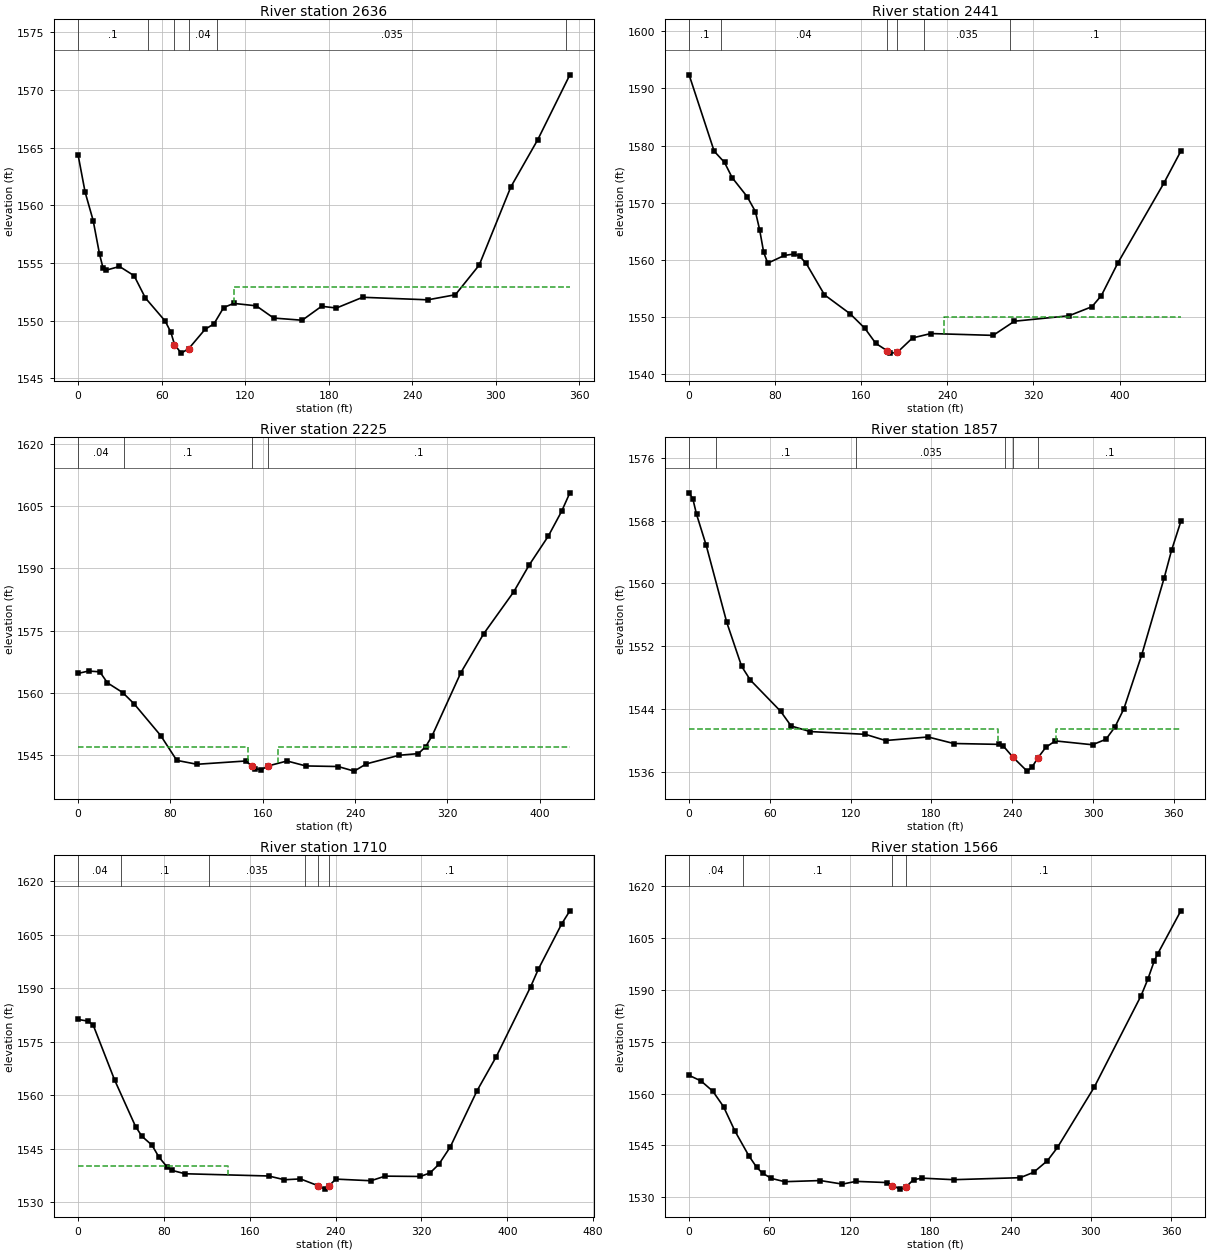
Type RM Length L Ch R = 1 ,2636    ,198.8,195.8,191.4
XS GIS Cut Line= 2
2064781.43734142267804.0657422342064569.57025129268086.565208709
#Sta/Elev= 30
       0 1564.34       5 1561.14    10.8 1558.67    15.4 1555.74    17.8  1554.6
    20.1 1554.37    29.7 1554.69    40.2 1553.89    48.3 1551.96    62.5 1549.96
    66.6 1548.99    69.21547.922      74 1547.18    79.41547.565    91.2 1549.25
    97.5 1549.71   104.5 1551.13   111.7 1551.49   127.9 1551.28   140.4 1550.22
   160.9 1550.03   174.8 1551.24   185.5 1551.09   204.3 1552.02   251.1  1551.8
   270.9 1552.24     288 1554.81   310.7 1561.58   330.1 1565.69   353.1  1571.3
#Mann= 6 ,-1 , 0
       0      .1       0      50     .04       0    69.2    .045       0
    79.4     .04       0     100    .035       0     350      .1       0
#XS Ineff= 2 , 0
                          111.77         1552.95
Permanent Ineff=
       F       F
Bank Sta=69.2,79.4
XS Rating Curve= 0 ,0
Exp/Cntr(USF)=0,0
Exp/Cntr=0.3,0.1

Type RM Length L Ch R = 1 ,2441    ,205.2,215.6,225.2
XS GIS Cut Line= 4
 2064675.3800772267648.1843955542064591.86905399 267699.10575117
2064528.04762161267927.233424331 2064435.7102301  268007.3496905
#Sta/Elev= 30
       0 1592.38    23.3    1579    32.9 1577.04      40 1574.37    53.9 1571.05
    61.6 1568.43    65.5 1565.28    69.3 1561.29    73.1 1559.39    88.5 1560.74
    97.8    1561   102.6 1560.61   108.8 1559.35   125.8 1553.84   149.7 1550.51
   163.3 1547.98   173.5 1545.33     1841544.055   187.1 1543.63   193.41543.753
   207.6 1546.29   224.6 1547.06   282.5 1546.74   302.3 1549.22   352.9 1550.17
   374.3 1551.76   383.1 1553.72   398.2 1559.36   441.3 1573.46   456.9 1579.01
#Mann= 6 ,-1 , 0
       0      .1       0      30     .04       0     184    .045       0
   193.4      .1       0  217.81    .035       0  297.81      .1       0
#XS Ineff= 2 , 0
                          237.18            1550
Permanent Ineff=
       F       F
Bank Sta=184,193.4
XS Rating Curve= 0 ,0
Exp/Cntr(USF)=0,0
Exp/Cntr=0.3,0.1

Type RM Length L Ch R = 1 ,2225    ,344.5,368.1,370.3
XS GIS Cut Line= 5
2064592.33413205267628.6406588832064522.19571159267634.389709741
2064320.97893156267707.9775607222064268.08766367 267779.26579136
2064231.29373818267817.209527022
#Sta/Elev= 30
       0 1564.69       9 1565.26    18.8 1565.07    25.4 1562.42    38.6 1560.08
    48.5 1557.37    71.6 1549.71    85.5 1543.75     103 1542.81   145.3  1543.6
   150.4 1542.42     153 1541.75   158.9 1541.49   164.21542.378   181.1  1543.6
   197.3 1542.41   225.3 1542.27   239.3 1541.16   249.7  1542.9   278.3 1544.98
   294.9 1545.38   301.2 1547.04   306.7  1549.6   331.7 1564.86   351.5 1574.23
   377.6 1584.35   390.7 1590.68   407.5 1597.74   419.1 1603.74   426.2 1608.17
#Mann= 4 ,-1 , 0
       0     .04       0      40      .1       0   150.4    .045       0
   164.2      .1       0
#XS Ineff= 2 , 0
           147.2    1547  173.42            1547
Permanent Ineff=
       F       F
Bank Sta=150.4,164.2
XS Rating Curve= 0 ,0
Exp/Cntr(USF)=0,0
Exp/Cntr=0.3,0.1

Type RM Length L Ch R = 1 ,1857    ,153.6,146.5,142.4
XS GIS Cut Line= 4
 2064579.6155562267547.984902895 2064515.5059616267552.561744798
2064302.57238536267472.9680766082064230.08179326267485.716055717
#Sta/Elev= 30
       0 1571.55     2.8 1570.77     5.5 1568.83    12.7 1564.86      28 1555.03
      39 1549.45    45.5 1547.69    67.9 1543.73    75.8 1541.84    89.9 1541.13
   130.9 1540.78   145.9 1539.99   177.5 1540.44   196.5 1539.61     230  1539.5
   233.5 1539.26   240.5 1537.87     251 1536.09   254.5 1536.56   259.1 1537.79
     265 1539.14     272 1539.94   299.6 1539.45   309.6 1540.15   316.3 1541.72
   322.9 1544.03   336.2 1550.93   352.9 1560.75   358.3 1564.22   365.2  1567.9
#Mann= 6 ,-1 , 0
       0     .04       0      20      .1       0  124.27    .035       0
  234.27      .1       0   240.5    .045       0   259.1      .1       0
#XS Ineff= 2 , 0
          229.18 1541.48  272.68         1541.48
Permanent Ineff=
       F       F
Bank Sta=240.5,259.1
XS Rating Curve= 0 ,0
Exp/Cntr(USF)=0,0
Exp/Cntr=0.3,0.1

Type RM Length L Ch R = 1 ,1710    ,145.1,144.4,143.3
XS GIS Cut Line= 4
2064546.34172519267268.7500751792064481.95235558267334.289254959
2064247.39108058267349.2367871892064126.66101256 267400.97824491
#Sta/Elev= 30
       0 1581.29     9.5  1580.8    14.1 1579.67      34 1564.32    53.6 1551.24
    59.5 1548.53    68.8 1546.06    75.4 1542.67    82.9 1539.96    87.6 1538.98
    99.6 1538.04   177.6 1537.41   192.3 1536.36   207.2 1536.59   223.31534.727
   230.2 1533.73   233.5 1534.54   240.1 1536.54   272.9 1536.08   286.1 1537.37
     319 1537.28     328 1538.28   336.1 1540.65   346.8 1545.53   371.8 1561.31
   389.7 1570.85   421.8 1590.48   428.9 1595.36   450.7 1608.07   458.3 1611.73
#Mann= 6 ,-1 , 0
       0     .04       0      40      .1       0  121.88    .035       0
  211.88      .1       0   223.3    .045       0   233.5      .1       0
#XS Ineff= 2 , 0
             140  1540.1
Permanent Ineff=
       F       F
Bank Sta=223.3,233.5
XS Rating Curve= 0 ,0
Exp/Cntr(USF)=0,0
Exp/Cntr=0.3,0.1

Type RM Length L Ch R = 1 ,1566    ,181.6,178.2,173.7
XS GIS Cut Line= 4
2064442.69115326267173.2966651142064400.52759007267206.992051591
2064199.95847732267236.6789896392064098.58055829267280.346396847
#Sta/Elev= 30
       0 1565.27     8.9 1563.66    17.7 1560.69    25.7 1556.23    34.1 1549.26
    44.6 1542.02    50.4 1538.72    54.8 1536.98    61.5 1535.47    71.4 1534.53
    97.9 1534.86   114.5 1533.83   124.5 1534.62   147.7 1534.28   151.81533.407
   157.6 1532.38   161.71532.939   167.6 1535.13   174.2 1535.55   197.4 1535.11
   247.2 1535.69   257.2 1537.24   267.5  1540.6     275 1544.43   302.4 1561.81
   337.4 1588.29   342.4    1593   347.3 1598.39   349.8 1600.37   367.1 1612.84
#Mann= 4 ,-1 , 0
       0     .04       0      40      .1       0   151.8    .045       0
   161.7      .1       0
Bank Sta=151.8,161.7
XS Rating Curve= 0 ,0
Exp/Cntr(USF)=0,0
Exp/Cntr=0.3,0.1

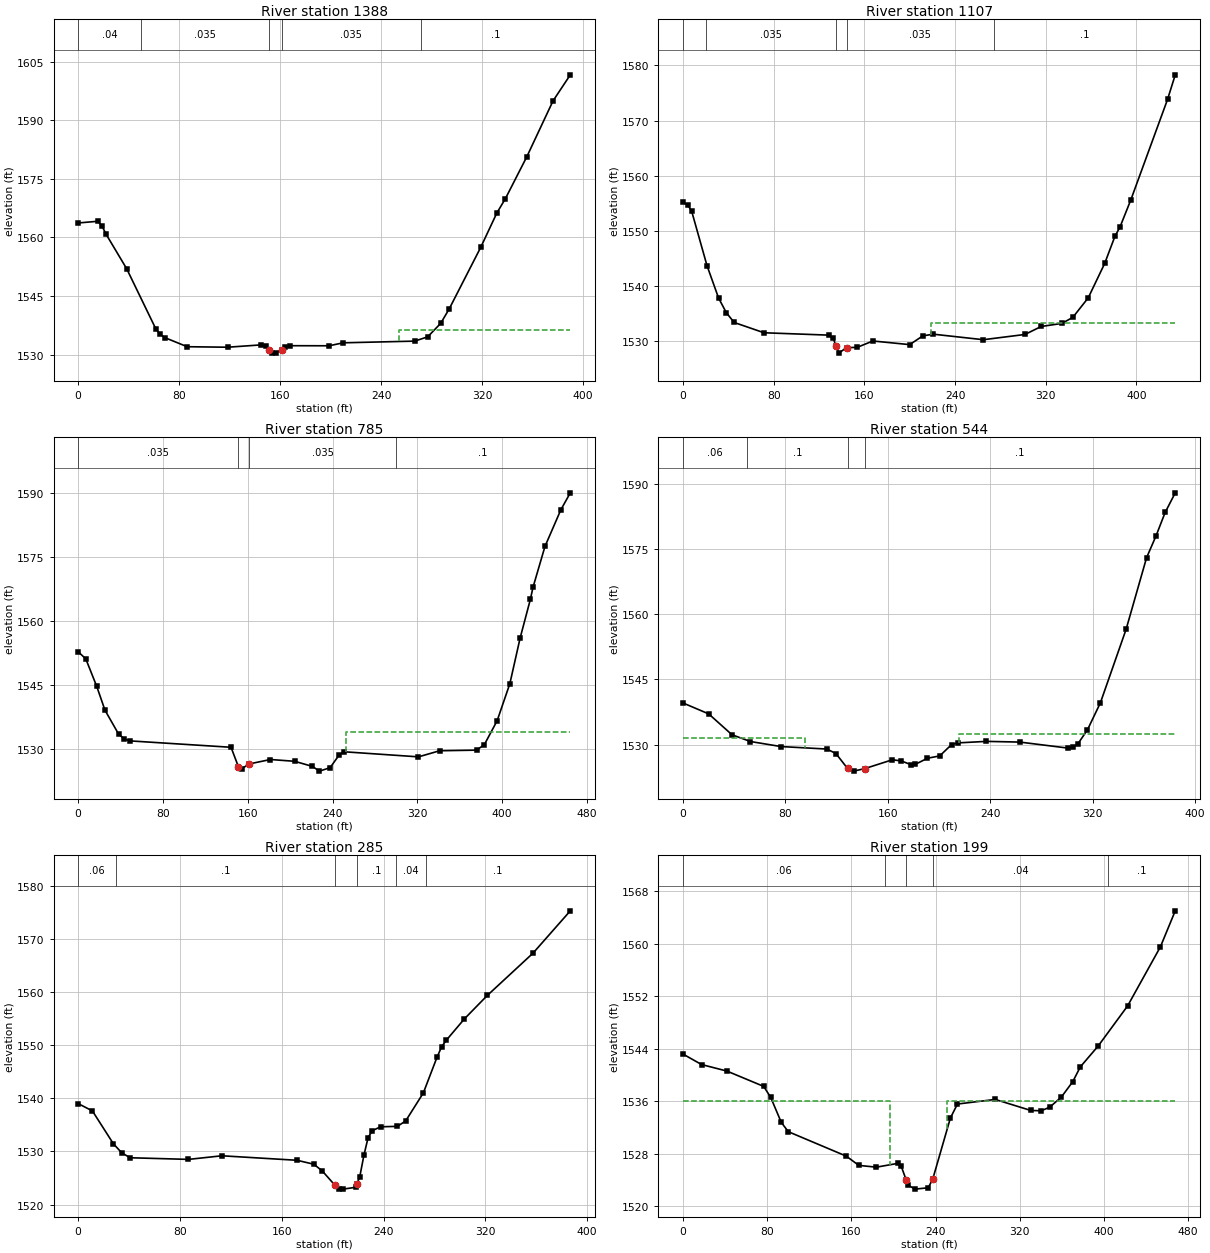
Type RM Length L Ch R = 1 ,1388    ,280.3,280.8,279.9
XS GIS Cut Line= 4
2064405.32478354267013.4865352382064341.73149285267010.371555301
2064171.45731474267111.6653650522064048.63132072 267148.51316326
#Sta/Elev= 30
       0 1563.71    15.5 1564.14    18.8 1563.01    22.1 1560.85    38.5 1551.98
    61.5 1536.65    64.8 1535.27    68.8 1534.37    86.4 1532.06   118.4 1531.93
   145.1 1532.53   148.6 1532.14     151 1531.11   153.4 1530.42   156.6 1530.47
   161.21531.307   164.2 1532.08     168 1532.32   198.9  1532.3     210 1533.06
   266.7 1533.49     277 1534.59   287.3 1538.04   294.1 1541.77     319 1557.47
   331.8 1566.27   338.6 1569.95   355.6 1580.69   376.3 1594.93     390  1601.6
#Mann= 5 ,-1 , 0
       0     .04       0      50    .035       0     151    .045       0
   161.2    .035       0   271.8      .1       0
#XS Ineff= 2 , 0
                          254.16         1536.42
Permanent Ineff=
       F       F
Bank Sta=151,161.2
XS Rating Curve= 0 ,0
Exp/Cntr(USF)=0,0
Exp/Cntr=0.3,0.1

Type RM Length L Ch R = 1 ,1107    ,321.7,321.6,321.7
XS GIS Cut Line= 4
2064374.19752668266813.1969755022064331.44215763  266824.2571331
 2064159.9935553266977.375611585 2064046.9936408267091.194366048
#Sta/Elev= 30
       0 1555.18     4.2 1554.69     7.6 1553.57    21.1 1543.73    31.3 1537.87
    38.1 1535.23      45 1533.44    71.4 1531.57   128.6 1531.14   132.6 1530.57
     135 1529.11   137.4 1527.88   144.3 1528.88   153.6 1528.92   167.5 1530.08
     200 1529.42   211.6 1531.01   220.9 1531.31     265 1530.31   301.7 1531.26
   316.1 1532.71   334.3 1533.26     344 1534.36   357.6  1537.9   372.1 1544.12
   381.1 1549.01   385.7 1550.77   395.2 1555.65   427.6 1573.85   434.4  1578.3
#Mann= 5 ,-1 , 0
       0     .06       0      20    .035       0     135    .045       0
   144.3    .035       0  274.03      .1       0
#XS Ineff= 2 , 0
                          219.15         1533.34
Permanent Ineff=
       F       F
Bank Sta=135,144.3
XS Rating Curve= 0 ,0
Exp/Cntr(USF)=0,0
Exp/Cntr=0.3,0.1

Type RM Length L Ch R = 1 ,785     ,241.8,241.8,241.8
XS GIS Cut Line= 6
2064357.28590118266766.025834637 2064270.7250379266794.063524019
2064253.34131076266800.5061801882064008.21854695  266845.4639635
2063923.10191689266893.1904296192063915.90793449266896.477937249
#Sta/Elev= 30
       0 1552.85     7.2 1551.19    17.5 1544.76    25.3 1539.17    38.2 1533.56
    43.5 1532.46    48.7 1531.99   144.2 1530.49   151.11525.977   154.2 1525.46
   161.3 1526.59   181.4 1527.63   204.2 1527.21   220.9 1526.02   227.6 1524.91
   237.6 1525.71   246.3 1528.72   250.9 1529.44     321 1528.25     341 1529.68
   375.8 1529.82   383.1  1531.1   395.2 1536.71   407.2  1545.4   416.8 1555.99
   426.5 1565.08     429 1567.91   440.3 1577.49   455.3 1586.08   464.2 1590.04
#Mann= 4 ,-1 , 0
       0    .035       0   151.1    .045       0   161.3    .035       0
  299.53      .1       0
#XS Ineff= 2 , 0
                          252.39         1533.97
Permanent Ineff=
       F       F
Bank Sta=151.1,161.3
XS Rating Curve= 0 ,0
Exp/Cntr(USF)=0,0
Exp/Cntr=0.3,0.1

Type RM Length L Ch R = 1 ,544     ,238.7,259.1,264.8
XS GIS Cut Line= 3
2064200.93555331266623.6367487922064013.42120243266801.325020148
2063903.69664777266863.556857121
#Sta/Elev= 30
       0 1539.57      20 1537.06    38.2 1532.25    52.6 1530.69    76.4 1529.53
   112.4 1528.95   119.4 1527.91   128.5 1524.47   133.3 1523.86     142 1524.45
   163.5 1526.48   170.5 1526.21   178.2 1525.33   181.4 1525.42   190.9 1526.83
   200.5 1527.37   209.8    1530   214.5 1530.37   236.9 1530.72   263.1 1530.56
   300.8 1529.17   304.6 1529.37   308.4 1530.14   315.9 1533.38     326 1539.61
   346.1 1556.57   362.1 1573.09   369.4 1578.06   376.6 1583.52   384.5 1588.05
#Mann= 4 ,-1 , 0
       0     .06       0      50      .1       0   128.5    .045       0
     142      .1       0
#XS Ineff= 2 , 0
           95.32 1531.61  215.44         1532.31
Permanent Ineff=
       F       F
Bank Sta=128.5,142
XS Rating Curve= 0 ,0
Exp/Cntr(USF)=0,0
Exp/Cntr=0.3,0.1

Type RM Length L Ch R = 1 ,285     ,81.5,85.5,81.8
XS GIS Cut Line= 4
2064191.10947379266611.3541493892064021.38955845266606.886199096
 2063928.0043951266603.3842654192063815.26193207266653.933827318
#Sta/Elev= 30
       0 1539.01    11.2 1537.63    27.7 1531.44    34.2 1529.75    40.8 1528.81
    86.7  1528.5     113 1529.18   172.1 1528.33   185.2 1527.59   191.8 1526.34
   201.6 1523.69   204.9 1522.92   208.2  1522.9     218 1523.24     219 1523.84
   221.3 1525.19   224.6 1529.29   227.9 1532.62   231.2 1533.91   237.7 1534.64
   250.9 1534.72   257.4 1535.74   271.3 1541.02     282 1547.71   285.6 1549.67
   289.2  1550.9   303.6 1554.97   321.6 1559.38   357.5 1567.34   386.8 1575.31
#Mann= 6 ,-1 , 0
       0     .06       0      30      .1       0   201.6    .045       0
     219      .1       0  249.78     .04       0  273.23      .1       0
Bank Sta=201.6,219
XS Rating Curve= 0 ,0
Exp/Cntr(USF)=0,0
Exp/Cntr=0.5,0.3

Type RM Length L Ch R = 1 ,199     ,73.1,73.1,76.1
XS GIS Cut Line= 4
 2064240.2398714 266617.086029112064181.28339427266576.144031102
2063963.47196486266531.9266732532063806.25469251266605.622269668
#Sta/Elev= 30
       0 1543.19    17.6  1541.6    41.6 1540.61    76.6 1538.27    83.3 1536.58
    93.3 1532.78     100 1531.36   155.1 1527.63     167 1526.22   183.7 1525.95
   203.8 1526.52   207.1 1526.18   211.9 1524.04   213.8  1523.2   220.5  1522.6
     233 1522.81   237.3 1524.16     254 1533.44   260.7 1535.58   296.6 1536.28
   330.4  1534.6   340.3 1534.55   348.4  1535.1   359.4 1536.63   370.3 1538.99
   377.5 1541.25   394.4 1544.42   422.4 1550.54   453.6 1559.56   467.7 1565.05
#Mann= 5 ,-1 , 0
       0     .06       0  191.78     .04       0   211.9    .045       0
   237.3     .04       0  404.03      .1       0
#XS Ineff= 2 , 0
             197    1536     251            1536
Permanent Ineff=
       F       F
Bank Sta=211.9,237.3
XS Rating Curve= 0 ,0
Exp/Cntr(USF)=0,0
Exp/Cntr=0.5,0.3

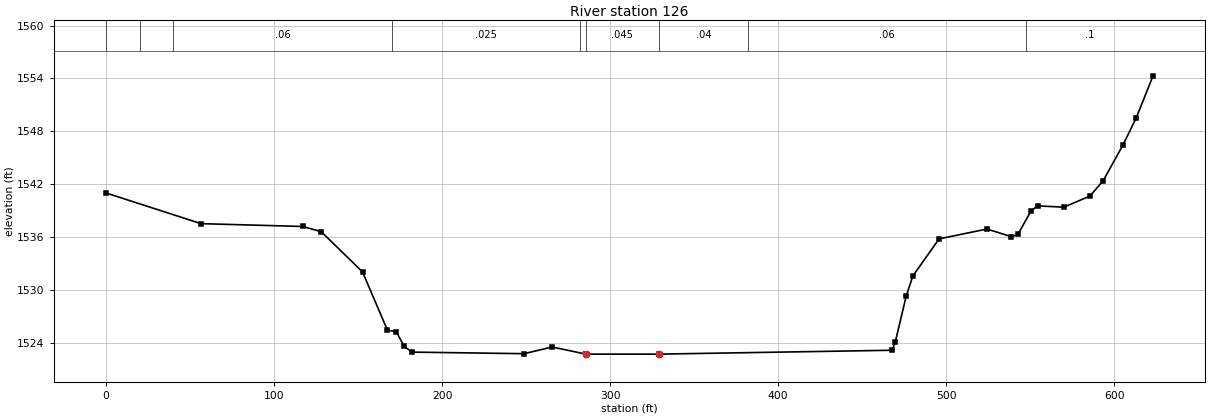
Type RM Length L Ch R = 1 ,126     ,,,
XS GIS Cut Line= 5
2064292.64562885 266617.086029112064156.71819546266495.897715006
2063959.63521653266457.6181980552063876.95384235 266439.34126271
2063792.53180766266569.890800891
#Sta/Elev= 30
       0    1541    56.6 1537.51     117 1537.19   128.1  1536.6   152.7 1532.02
   167.5 1525.41   172.8 1525.23   177.4 1523.58   182.1 1522.92   248.8 1522.74
   265.5  1523.5   285.4  1522.7   285.6 1522.69     329 1522.69   467.6 1523.13
   469.6 1524.04   476.1 1529.26   480.1 1531.57   495.7 1535.78   524.2  1536.9
   538.7 1536.03   542.6 1536.29   550.4 1538.95   554.3 1539.53   569.9 1539.38
   585.5 1540.65   593.4 1542.41   605.1 1546.45   612.9 1549.48     623  1554.3
#Mann= 9 ,-1 , 0
       0     .06       0      20    .025       0      40     .06       0
     170    .025       0  282.11     .04       0   285.4    .045       0
     329     .04       0  382.11     .06       0  547.55      .1       0
Bank Sta=285.4,329
XS Rating Curve= 0 ,0
Exp/Cntr(USF)=0,0
Exp/Cntr=0.5,0.3
LCMann Table=0

Chan Stop Cuts=-1
Use User Specified Reach Order=0
Composite Channel Slope=5